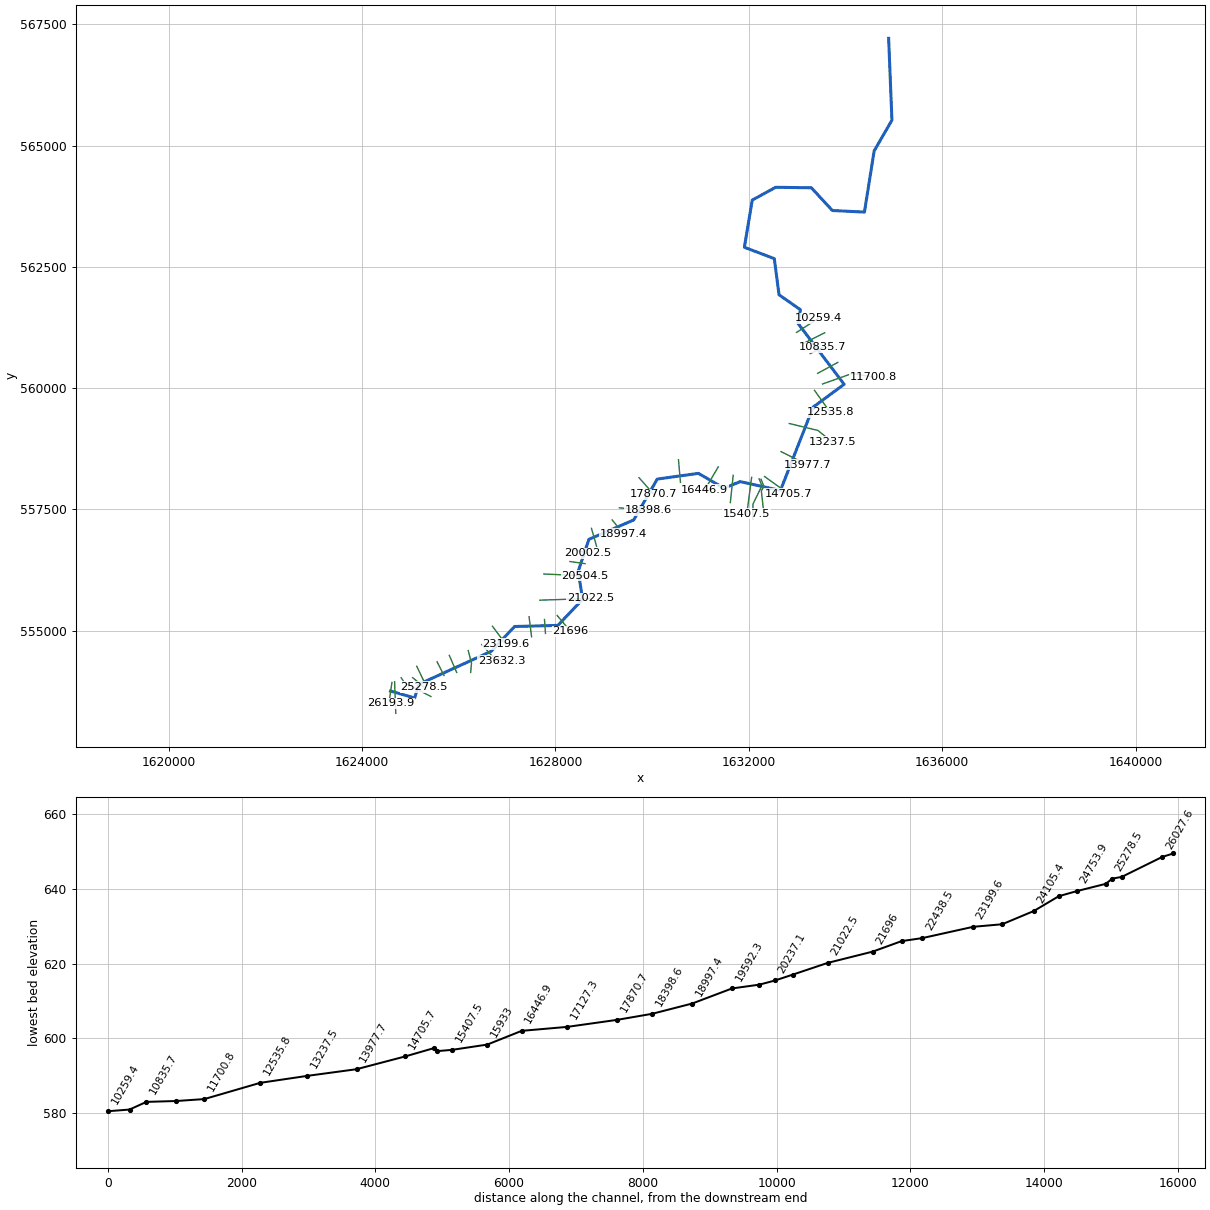
--- BryanCr.prj (project) ---

Proj Title=BryanCr
Current Plan=p01
Geom File=g01
Flow File=f01
Plan File=p01
DSS Export Rating Curves=0
DSS Export Rating Curve Sorted=0
DSS Export Volume Flow Curves=0
DXF OffsetX=0
DXF OffsetY=0
DXF ScaleX=0
DXF ScaleY=0

--- BryanCr.p01 (plan) ---

Plan Title=Floodplain
Program Version=4.00
Geom File=g01
Flow File=f01
K Sum by GR=0
Std Step Tol=0.01
Critical Tol=0.01
Num of Std Step Trials=20
Max Error Tol=0.3
Flow Tol Ratio=0.001
Split Flow NTrial=30
Split Flow Tol=0.02
Split Flow Ratio=0.02
Log Output Level=0
Friction Slope Method=1
Unsteady Friction Slope Method=2
Unsteady Bridges Friction Slope Method=1
Global Log Level=0
CheckData=False
Run HTab=0
Run UNet=0
Run PostProcess=0
UNET Theta=0
UNET Theta Warmup=0
UNET ZTol=0
UNET ZSATol=0
UNET MxIter=0
UNET MaxInSteps=0
UNET DtIC=0
UNET DtMin=0
UNET MaxCRTS=0
UNET WFStab=0
UNET SFStab=0
UNET WFX=0
UNET SFX=0
UNET DSS MLevel=0
UNET DZMax Abort=0
UNET Convert EG Bridges=0
UNET Use Existing IB Tables=0
UNET Froude Limit=0
UNET Froude Power=0
Write IC File=0
Echo Input=False
Echo Output=False
Write Detailed=0

--- BryanCr.f01 (steady flow) ---

Flow Title=NFF Regression Equation
Program Version=4.10
Number of Profiles= 1
Profile Names=P100yr
River Rch & RM=BryanCr,Main            ,26193.9
     995
River Rch & RM=BryanCr,Main            ,25420.9
     996
River Rch & RM=BryanCr,Main            ,24753.9
    1113
River Rch & RM=BryanCr,Main            ,23632.3
    1122
River Rch & RM=BryanCr,Main            ,23199.6
    1137
River Rch & RM=BryanCr,Main            ,21696
    1161
River Rch & RM=BryanCr,Main            ,21022.5
    1247
River Rch & RM=BryanCr,Main            ,20237.1
    1494
River Rch & RM=BryanCr,Main            ,17870.7
    1526
River Rch & RM=BryanCr,Main            ,17127.3
    1664
River Rch & RM=BryanCr,Main            ,16446.9
    1668
River Rch & RM=BryanCr,Main            ,15407.5
    1692
River Rch & RM=BryanCr,Main            ,13237.5
    1827
River Rch & RM=BryanCr,Main            ,11700.8
    1968
River Rch & RM=BryanCr,Main            ,10583
    1977
River Rch & RM=BryanCr,Main            ,7662.6
    2024
River Rch & RM=BryanCr,Main            ,7420.7
    2053
River Rch & RM=BryanCr,Main            ,6972
    2223
River Rch & RM=BryanCr,Main            ,5962.8
    2236
River Rch & RM=BryanCr,Main            ,3806
    2298
River Rch & RM=BryanCr,Main            ,3165.9
    2303
River Rch & RM=BryanCr,Main            ,1966.3
    2321
River Rch & RM=BryanCr,Main            ,1346.1
    2328
River Rch & RM=BryanCr,Main            ,467.9
    2337
River Rch & RM=BryanCr,Main            ,56.7
    2340
Boundary for River Rch & Prof#=BryanCr,Main            , 1
Up Type= 0
Dn Type= 3
Dn Slope=0.00164
DSS Import GetInterval= 0
DSS Import GetPeak= 0
DSS Import FillOption= 0

--- BryanCr.g01 (geometry) ---

Geom Title=USGS 10m DEM
Program Version=4.10

River Reach=BryanCr         ,Main
Reach XY= 30
     1624588.179      553752.458     1625087.808      553609.933
     1625171.096      553890.606     1626670.022      554571.336
     1627153.963      555083.488     1628049.879      555106.444
     1628561.024      555643.312     1628471.172      556226.414
     1628692.165       556881.86     1629616.785      557279.364
     1630105.391      558123.658     1630955.928       558241.84
     1631486.668      557935.682     1631821.532      558071.305
     1632653.029      557888.523     1633329.778      559607.763
     1633970.738      560078.627     1633015.603       561336.39
     1633067.686      561615.904     1632624.254      561924.643
     1632526.827      562669.829      1631907.61      562904.666
     1632070.565      563877.461     1632554.494      564141.646
     1633292.886      564131.417     1633727.279      563662.656
     1634390.976      563630.115     1634591.714      564889.881
     1634959.637      565526.836     1634891.447        567213.4

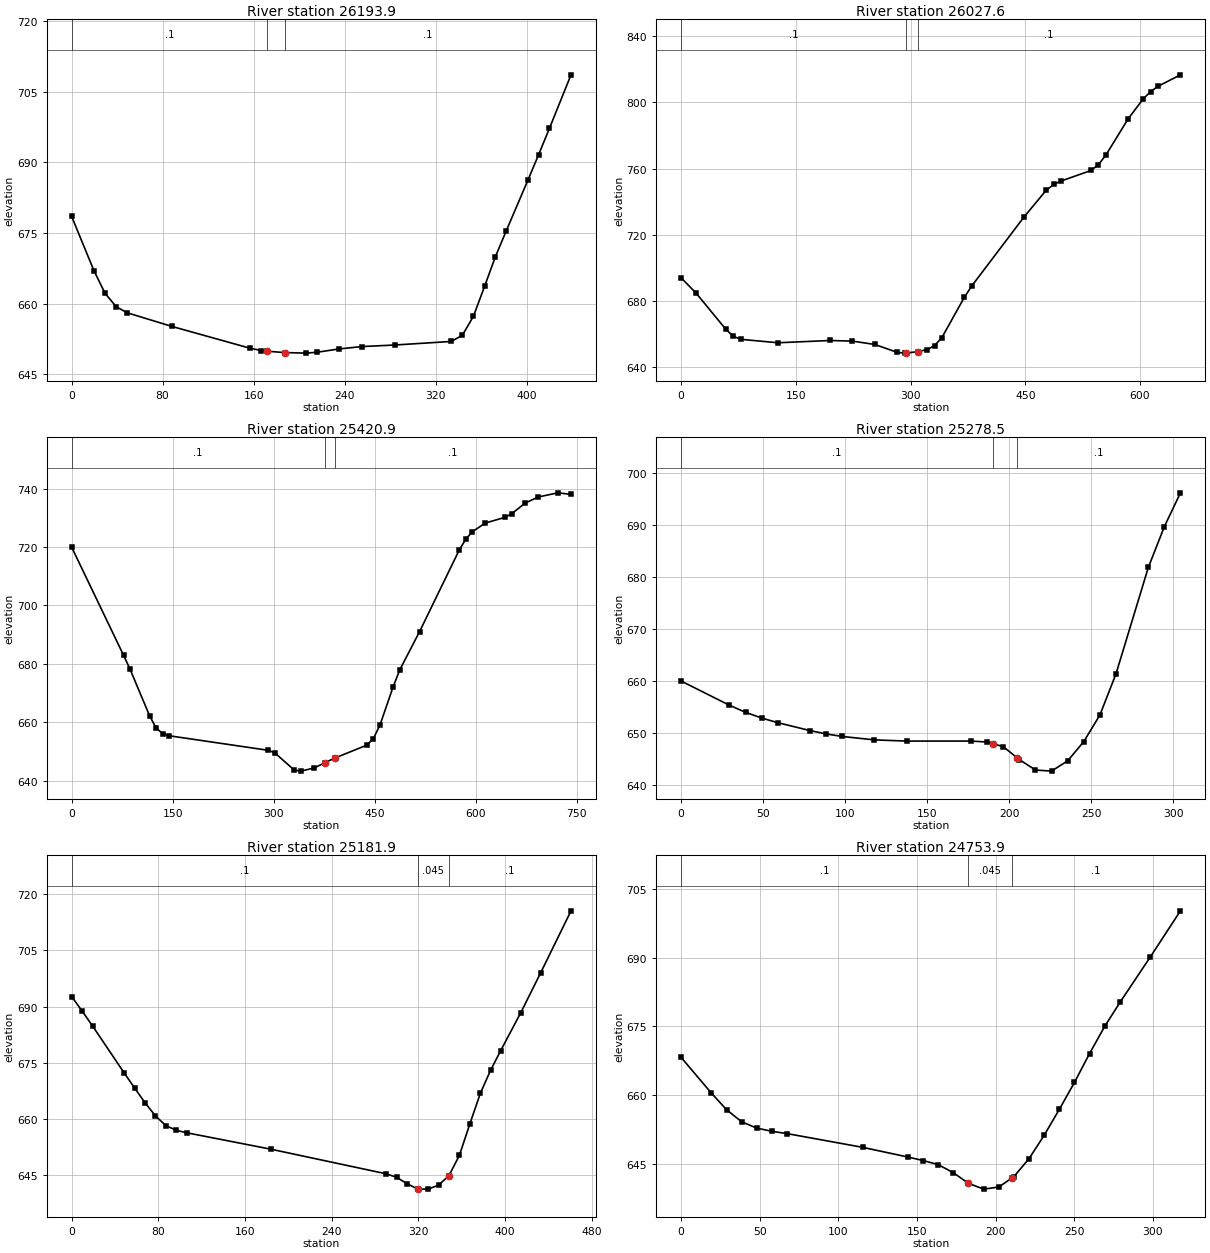
Type RM Length L Ch R = 1 ,26193.9 ,165.9,166.3,218.6
XS GIS Cut Line= 3
      1624616.94      553929.054     1624565.172      553569.634
     1624596.107      553500.235
#Sta/Elev= 25
       0  678.53    19.6  667.02    29.4  662.19    39.3  659.33    49.1  658.05
    88.3  655.16     157  650.53   166.8  650.05   172.2   649.9   187.2  649.62
   206.1   649.5   215.9  649.69   235.5   650.4   255.2  650.89   284.6  651.23
   333.7  651.98   343.5  653.27   353.3  657.33   363.1  663.68   372.6  669.97
   382.1  675.44   401.1  686.18   410.6  691.64   420.1  697.22   439.1   708.6
#Mann= 3 , 0 , 0
       0      .1       0   172.2    .045       0   187.2      .1       0
Bank Sta=172.2,187.2
XS Rating Curve= 0 ,0
Exp/Cntr=0.3,0.1

Type RM Length L Ch R = 1 ,26027.6 ,576.1,606.6,633.6
XS GIS Cut Line= 2
     1624672.621      553944.264     1624696.801      553291.901
#Sta/Elev= 30
       0  694.08    19.5   684.9    58.5  662.95    68.2  658.76      78  656.91
   126.7  654.83   194.9   656.2   224.1  655.82   253.3   653.8   282.6  649.02
   292.3  648.57   294.1  648.63   309.1  649.42   321.5   650.7   331.3  653.08
     341     658   370.2   682.2     380  689.14   448.2  730.72   477.4  746.98
   487.2  750.42   496.9  752.53   535.9  758.88   545.6  762.38   555.4  768.22
   584.6  790.17   604.1  802.11   613.8  806.51   623.6  809.75   652.8  816.64
#Mann= 3 , 0 , 0
       0      .1       0   294.1    .045       0   309.1      .1       0
Bank Sta=294.1,309.1
XS Rating Curve= 0 ,0
Exp/Cntr=0.3,0.1

Type RM Length L Ch R = 1 ,25420.9 ,146.6,142.5,137.5
XS GIS Cut Line= 3
     1624808.038      554027.597     1624877.482      553923.431
     1625424.232      553639.123
#Sta/Elev= 30
       0  719.98      77  682.96    86.7  678.15   115.6  662.27   125.2  658.06
     135  656.08   144.8  655.34   291.5  650.37   301.3  649.54   330.6  643.58
   340.4  643.22     360   644.3   375.6  646.06   390.6  647.69   438.2  652.12
     448  654.39   457.8  659.03   477.3   672.1   487.1   677.9   516.5  690.99
   575.2  718.88   584.9   722.6   594.7  725.24   614.3  728.24   643.6  730.21
   653.4  731.42     673  735.03   692.5  737.15   721.9  738.59   741.4  738.06
#Mann= 3 , 0 , 0
       0      .1       0   375.6    .045       0   390.6      .1       0
Bank Sta=375.6,390.6
XS Rating Curve= 0 ,0
Exp/Cntr=0.3,0.1

Type RM Length L Ch R = 1 ,25278.5 ,106.9,96.6,86
XS GIS Cut Line= 2
      1625045.76      554029.748     1625280.135      553835.304
#Sta/Elev= 25
       0  660.06    29.5   655.4    39.3  654.05    49.1  652.95    58.9  652.06
    78.6  650.54    88.4   649.9    98.2  649.41   117.9  648.75   137.5  648.52
   176.8  648.52   186.6  648.34     190  648.03   196.5  647.44     205  645.29
   206.3  644.96   216.1  642.96   225.9  642.75   235.8  644.75   245.6  648.44
   255.4  653.54   265.2  661.43   284.9  681.86   294.7  689.72   304.5   696.2
#Mann= 3 , 0 , 0
       0      .1       0     190    .045       0     205      .1       0
Bank Sta=190,205
XS Rating Curve= 0 ,0
Exp/Cntr=0.3,0.1

Type RM Length L Ch R = 1 ,25181.9 ,427.2,428,428.5
XS GIS Cut Line= 3
     1625130.955      554263.709     1625294.149      553923.431
     1625356.649      553867.875
#Sta/Elev= 26
       0  692.72     9.7  688.84    19.4  684.83    48.4  672.39    58.1  668.33
    67.7  664.42    77.4  660.87    87.1  658.28    96.8  657.03   106.4  656.38
   183.9  652.01   290.3  645.45     300  644.51   309.6  642.82   319.3   641.4
     329  641.36   338.7  642.42   348.4  644.99     358   650.4   367.7  658.83
   377.4  666.99   386.7  673.02     396  678.25   414.6   688.4   433.1  699.11
     461  715.57
#Mann= 3 , 0 , 0
       0      .1       0   319.3    .045       0   348.4      .1       0
Bank Sta=319.3,348.4
XS Rating Curve= 0 ,0
Exp/Cntr=0.3,0.1

Type RM Length L Ch R = 1 ,24753.9 ,276.7,275.3,273.9
XS GIS Cut Line= 2
     1625550.968      554356.137     1625695.065      554073.151
#Sta/Elev= 26
       0  668.23    19.2  660.45    28.9   656.8    38.5  654.16    48.1  652.77
    57.7  652.08    67.4  651.57   115.5  648.57   144.4  646.44     154  645.68
   163.6  644.79   173.2  643.01   182.8   640.7   192.5  639.44   202.1   639.9
   210.4  641.87   211.7  642.18   221.3   646.1     231  651.24   240.6  656.89
   250.2  662.75   259.8  669.07   269.4  674.98   279.1  680.22   298.3  690.09
   317.6  700.24
#Mann= 3 , 0 , 0
       0      .1       0   182.8    .045       0   210.4      .1       0
Bank Sta=182.8,210.4
XS Rating Curve= 0 ,0
Exp/Cntr=0.3,0.1

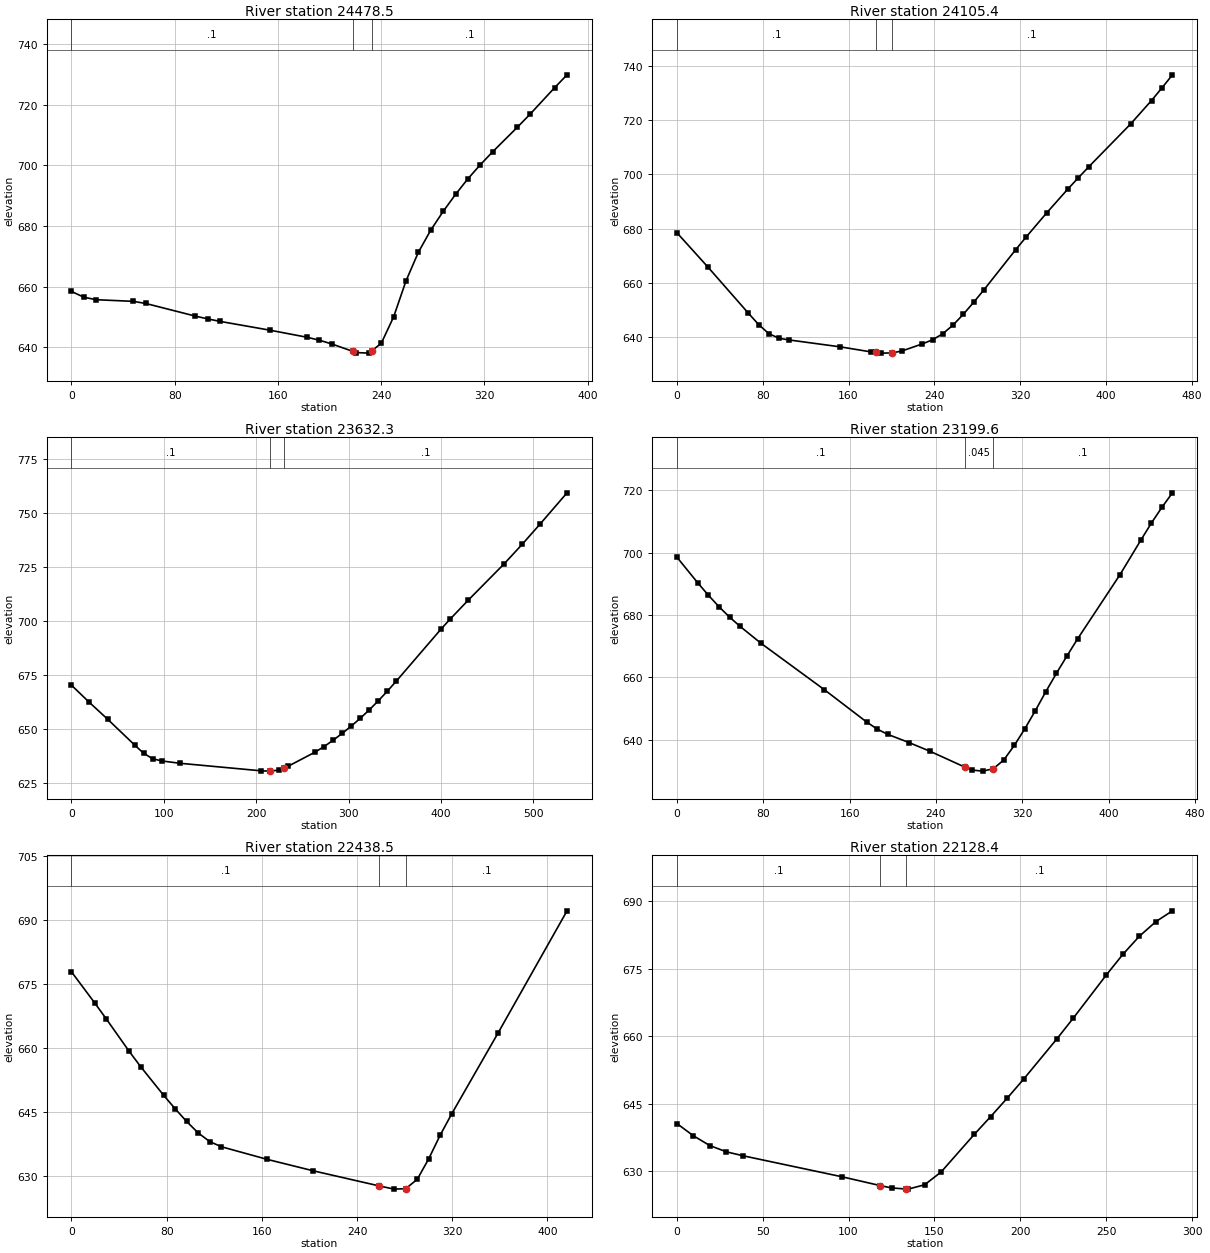
Type RM Length L Ch R = 1 ,24478.5 ,376.6,373.1,369.6
XS GIS Cut Line= 2
      1625804.44      554488.082     1625957.218      554135.651
#Sta/Elev= 30
       0   658.4     9.6  656.48    19.2  655.66      48  655.12    57.6  654.42
      96  650.26   105.6  649.34   115.2  648.51   153.6  645.63   182.5  643.29
   192.1  642.32   201.7  641.08   217.9  638.66   220.9  638.23   230.5  638.05
   232.9  638.86   240.1  641.27   249.7     650   259.3  661.87   268.9  671.33
   278.5  678.62   288.1  684.78   297.7  690.39   307.3  695.55   316.9  700.17
   326.5  704.45   345.7  712.58   355.3  716.76   374.5  725.58   384.1  729.81
#Mann= 3 , 0 , 0
       0      .1       0   217.9    .045       0   232.9      .1       0
Bank Sta=217.9,232.9
XS Rating Curve= 0 ,0
Exp/Cntr=0.3,0.1

Type RM Length L Ch R = 1 ,24105.4 ,464.2,473.2,480.2
XS GIS Cut Line= 3
     1626195.065       554587.04     1626263.611      554329.088
     1626245.382      554135.078
#Sta/Elev= 30
       0  678.49    28.6  665.97    66.7  648.79    76.3  644.58    85.8  641.25
    95.3  639.55   104.9  638.93   152.5  636.39   181.1  634.53   185.4  634.33
   190.6  634.09   200.4  634.16   209.7  634.87   228.8   637.5   238.3     639
   247.8  641.23   257.4  644.44   266.9  648.38   276.6  652.82   286.4  657.53
   315.6  672.14   325.4  676.84   344.8  685.85   364.3  694.54   374.1   698.7
   383.8  702.74   422.8  718.52   442.3  727.18     452  731.81   461.8  736.65
#Mann= 3 , 0 , 0
       0      .1       0   185.4    .045       0   200.4      .1       0
Bank Sta=185.4,200.4
XS Rating Curve= 0 ,0
Exp/Cntr=0.3,0.1

Type RM Length L Ch R = 1 ,23632.3 ,434.9,432.7,435.6
XS GIS Cut Line= 3
     1626476.315      554710.304     1626678.975      554485.338
     1626884.705      554374.661
#Sta/Elev= 30
       0  670.31    19.5  662.31    39.1  654.59    68.4  642.62    78.1  638.82
    87.9  636.27    97.7  635.27   117.2  634.19   205.1   630.7   214.6  630.55
   224.6  631.02   229.6  631.92   234.4  632.78   263.7  639.34   273.5  641.93
   283.2  644.83     293  647.99   302.8  651.36   312.5  654.97   322.3  658.85
     332  663.03   341.7  667.44   351.5  672.14   400.1   696.3   409.9  700.89
   429.3  709.57   468.3  726.44   487.7   735.4   507.2  744.84   536.4   759.3
#Mann= 3 , 0 , 0
       0      .1       0   214.6    .045       0   229.6      .1       0
Bank Sta=214.6,229.6
XS Rating Curve= 0 ,0
Exp/Cntr=0.3,0.1

Type RM Length L Ch R = 1 ,23199.6 ,774.1,761.1,746.2
XS GIS Cut Line= 2
     1626696.927      555090.097     1626971.232      554722.042
#Sta/Elev= 30
       0   698.6    19.5  690.27    29.3  686.32    39.1  682.64    48.8  679.34
    58.6  676.34    78.1  670.88   136.7     656   175.8  645.64   185.6  643.36
   195.3  641.68   214.9  639.06   234.4  636.26   266.6  631.18   273.5  630.21
   283.2  629.87     293  630.62   302.8  633.44   312.5   638.1   322.3  643.46
   332.1  649.32   341.8  655.43   351.6   661.3   361.4   666.9   371.1   672.3
   410.2  692.82   429.7  704.01   439.5  709.52   449.3  714.59     459  719.23
#Mann= 3 , 0 , 0
       0      .1       0   266.6    .045       0     293      .1       0
Bank Sta=266.6,293
XS Rating Curve= 0 ,0
Exp/Cntr=0.3,0.1

Type RM Length L Ch R = 1 ,22438.5 ,311.5,310.1,308.5
XS GIS Cut Line= 2
     1627453.871      555284.542     1627505.955      554871.347
#Sta/Elev= 22
       0   677.8    19.4  670.56    29.1  666.82    48.4   659.2    58.1  655.58
    77.5  648.84    87.2  645.67    96.8  642.71   106.5  640.03   116.2     638
   125.9  636.79   164.6  633.82   203.4  631.13   258.8  627.59   271.2  626.85
   280.9  626.96   290.6  629.14   300.2  633.93   309.9  639.51   319.6  644.51
   358.4  663.39   416.5  692.09
#Mann= 3 , 0 , 0
       0      .1       0   258.8    .045       0   280.9      .1       0
Bank Sta=258.8,280.9
XS Rating Curve= 0 ,0
Exp/Cntr=0.3,0.1

Type RM Length L Ch R = 1 ,22128.4 ,417.7,432.3,447
XS GIS Cut Line= 2
      1627773.19      555227.665     1627793.559      554939.765
#Sta/Elev= 23
       0  640.61     9.6   637.9    19.2  635.71    28.9  634.32    38.5  633.45
    96.2  628.78   118.5  626.82   125.1   626.3   133.5  626.07   134.7  626.04
   144.3  627.01   153.9  629.84   173.2  638.19   182.8  642.16   192.4  646.24
     202  650.48   221.3  659.39   230.9  664.02   250.1  673.59   259.8  678.19
   269.4  682.21     279  685.44   288.6  687.83
#Mann= 3 , 0 , 0
       0      .1       0   118.5    .045       0   133.5      .1       0
Bank Sta=118.5,133.5
XS Rating Curve= 0 ,0
Exp/Cntr=0.3,0.1

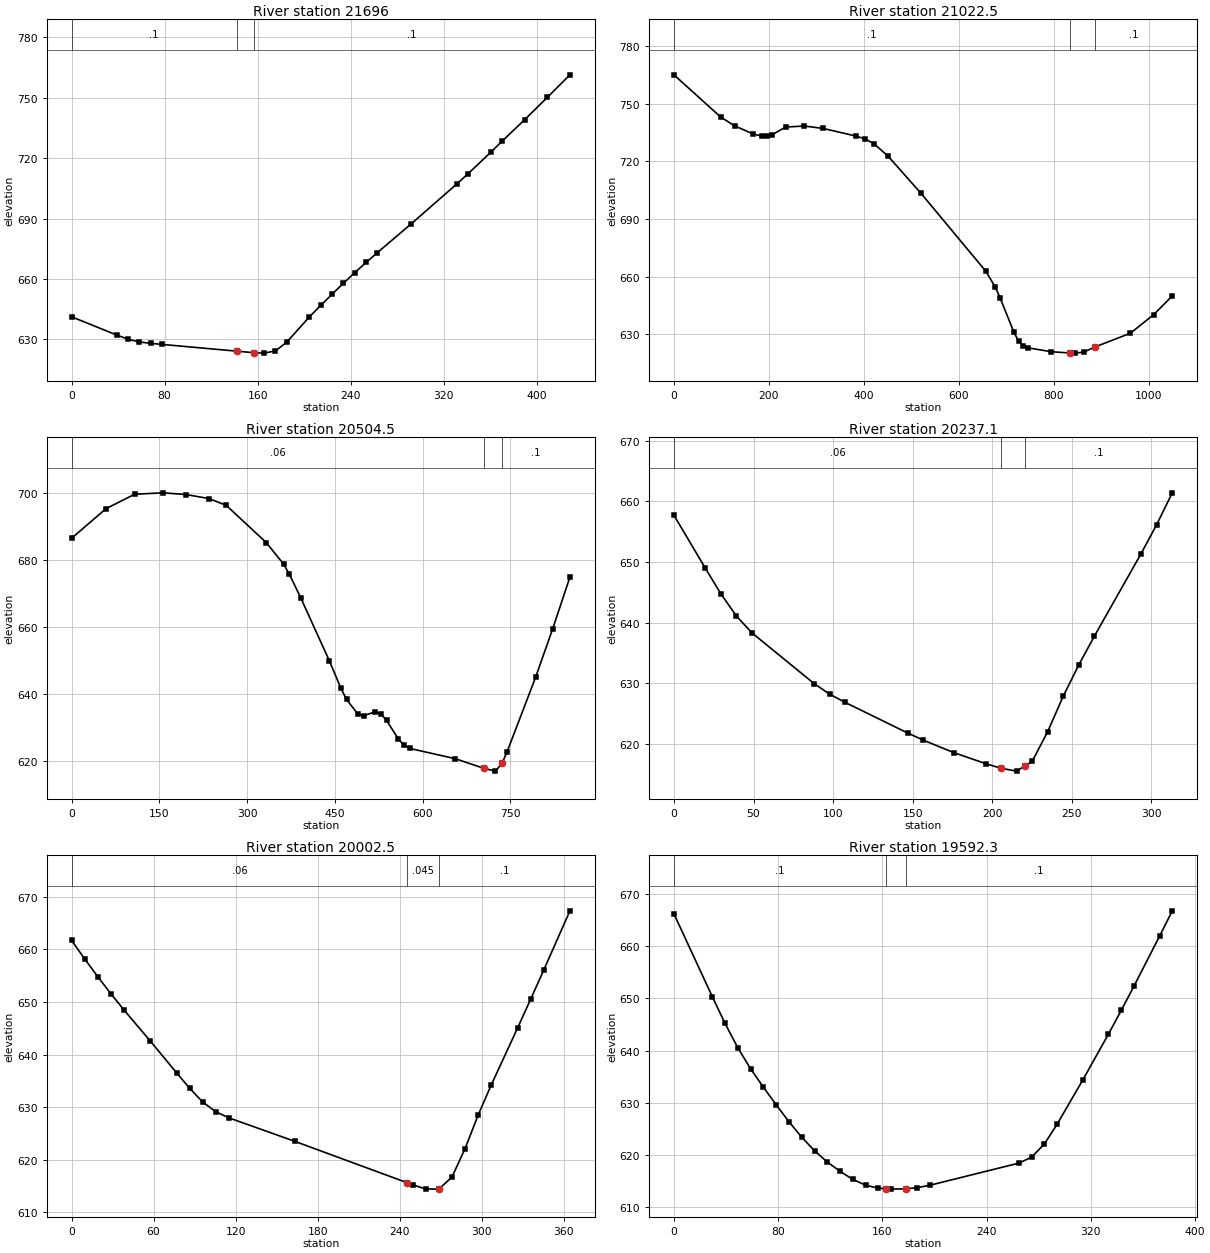
Type RM Length L Ch R = 1 ,21696   ,658.7,673.5,691.3
XS GIS Cut Line= 2
     1628035.473      555310.423      1628311.51      554982.459
#Sta/Elev= 26
       0  641.25      39  632.17    48.7  630.11    58.4  628.77    68.2  628.09
    77.9  627.55   141.9  624.22   156.9  623.44   165.6  623.23   175.4  624.34
   185.1  628.67   204.6  641.22   214.3  646.88   224.1  652.46   233.8  657.88
   243.6  663.18   253.3  668.18     263  673.06   292.3  687.42   331.2  707.04
     341  712.18   360.5  722.81   370.2  728.26   389.7  738.98   409.2  750.04
   428.7  761.26
#Mann= 3 , 0 , 0
       0      .1       0   141.9    .045       0   156.9      .1       0
Bank Sta=141.9,156.9
XS Rating Curve= 0 ,0
Exp/Cntr=0.3,0.1

Type RM Length L Ch R = 1 ,21022.5 ,510.9,518.1,518.2
XS GIS Cut Line= 2
     1627678.264      555626.556     1628726.875      555661.278
#Sta/Elev= 30
       0  764.93      98  743.06   127.5  738.42   166.7  734.19   186.3  732.97
   196.1  733.07   205.9  733.66   235.3  737.79   274.6   738.3   313.8  737.06
   382.4  733.13     402  731.66   421.6  729.01     451  722.56   519.7  703.44
     657  662.67   676.6  654.46   686.4   649.1   715.8  631.02   725.6   626.4
   735.4  623.91   745.2  622.97   794.2  620.95   833.5  620.28   843.3  620.21
   862.9  620.73   885.9  623.38   960.9  630.55    1010  640.22  1049.2  649.99
#Mann= 3 , 0 , 0
       0      .1       0   833.5    .045       0   885.9      .1       0
Bank Sta=833.5,885.9
XS Rating Curve= 0 ,0
Exp/Cntr=0.3,0.1

Type RM Length L Ch R = 1 ,20504.5 ,269.5,267.3,265.2
XS GIS Cut Line= 2
     1627759.427      556166.486     1628610.121      556128.292
#Sta/Elev= 30
       0  686.42    58.7   695.2   107.7  699.52   156.6  699.94   195.8  699.42
   234.9  698.23   264.3  696.21   332.8  685.11   362.2  678.74   371.9  675.81
   391.5  668.72   440.5  649.94     460  641.86   469.8  638.43   489.4  634.06
   499.2  633.62   518.8  634.74   528.6  634.11   538.3   632.2   557.9  626.78
   567.7  624.84   577.5  623.88   655.8  620.79   704.7  617.92   724.3   617.1
   735.4  619.38   743.9  622.72   792.8  644.97   822.2   659.5   851.6  674.86
#Mann= 3 , 0 , 0
       0     .06       0   704.7    .045       0   735.4      .1       0
Bank Sta=704.7,735.4
XS Rating Curve= 0 ,0
Exp/Cntr=0.3,0.1

Type RM Length L Ch R = 1 ,20237.1 ,236.9,234.7,232.4
XS GIS Cut Line= 2
     1628301.094      556423.431     1628611.267      556379.869
#Sta/Elev= 23
       0  657.72    19.6  649.04    29.4   644.8    39.2  641.12    48.9  638.35
    88.1  629.95    97.9  628.21   107.7  626.84   146.8  621.82   156.6  620.64
   176.2  618.54   195.8  616.77   205.4     616   215.3  615.52   220.4  616.35
   225.1  617.11   234.9  622.04   244.7  627.91   254.5  633.08   264.3  637.81
   293.6   651.4   303.4  656.19   313.2  661.42
#Mann= 3 , 0 , 0
       0     .06       0   205.4    .045       0   220.4      .1       0
Bank Sta=205.4,220.4
XS Rating Curve= 0 ,0
Exp/Cntr=0.3,0.1

Type RM Length L Ch R = 1 ,20002.5 ,435,410.2,385.4
XS GIS Cut Line= 2
      1628311.51      556683.847     1628665.677      556597.042
#Sta/Elev= 24
       0  661.72     9.6  658.17    19.2   654.8    28.8  651.55    38.4  648.46
    57.6  642.57    76.8  636.53    86.4  633.58      96  630.95   105.6  629.11
   115.2  627.95   163.1  623.51   245.6  615.61   249.5  615.22   259.1  614.44
   268.7   614.4   278.3   616.7   287.9  622.12   297.5  628.52   307.1  634.26
   326.3  645.05   335.9  650.55   345.5  656.11   364.6  667.34
#Mann= 3 , 0 , 0
       0     .06       0   245.6    .045       0   268.7      .1       0
Bank Sta=245.6,268.7
XS Rating Curve= 0 ,0
Exp/Cntr=0.3,0.1

Type RM Length L Ch R = 1 ,19592.3 ,585.6,594.8,603.9
XS GIS Cut Line= 2
     1628745.538      557107.459     1628849.705      556739.403
#Sta/Elev= 30
       0  666.26    29.4  650.37    39.2  645.22      49  640.54    58.8  636.51
    68.7  632.94    78.5  629.57    88.3  626.32    98.1  623.34   107.9  620.75
   117.7  618.59   127.5   616.8   137.3  615.25   147.1  614.13   156.9  613.56
   162.8  613.45   166.7  613.38   177.8  613.44   186.4  613.66   196.2  614.11
   264.8  618.38   274.6  619.54   284.4  622.08   294.2  625.89   313.9   634.4
   333.5  643.16   343.3   647.7   353.1  652.39   372.7  661.96   382.5  666.84
#Mann= 3 , 0 , 0
       0      .1       0   162.8    .045       0   177.8      .1       0
Bank Sta=162.8,177.8
XS Rating Curve= 0 ,0
Exp/Cntr=0.3,0.1

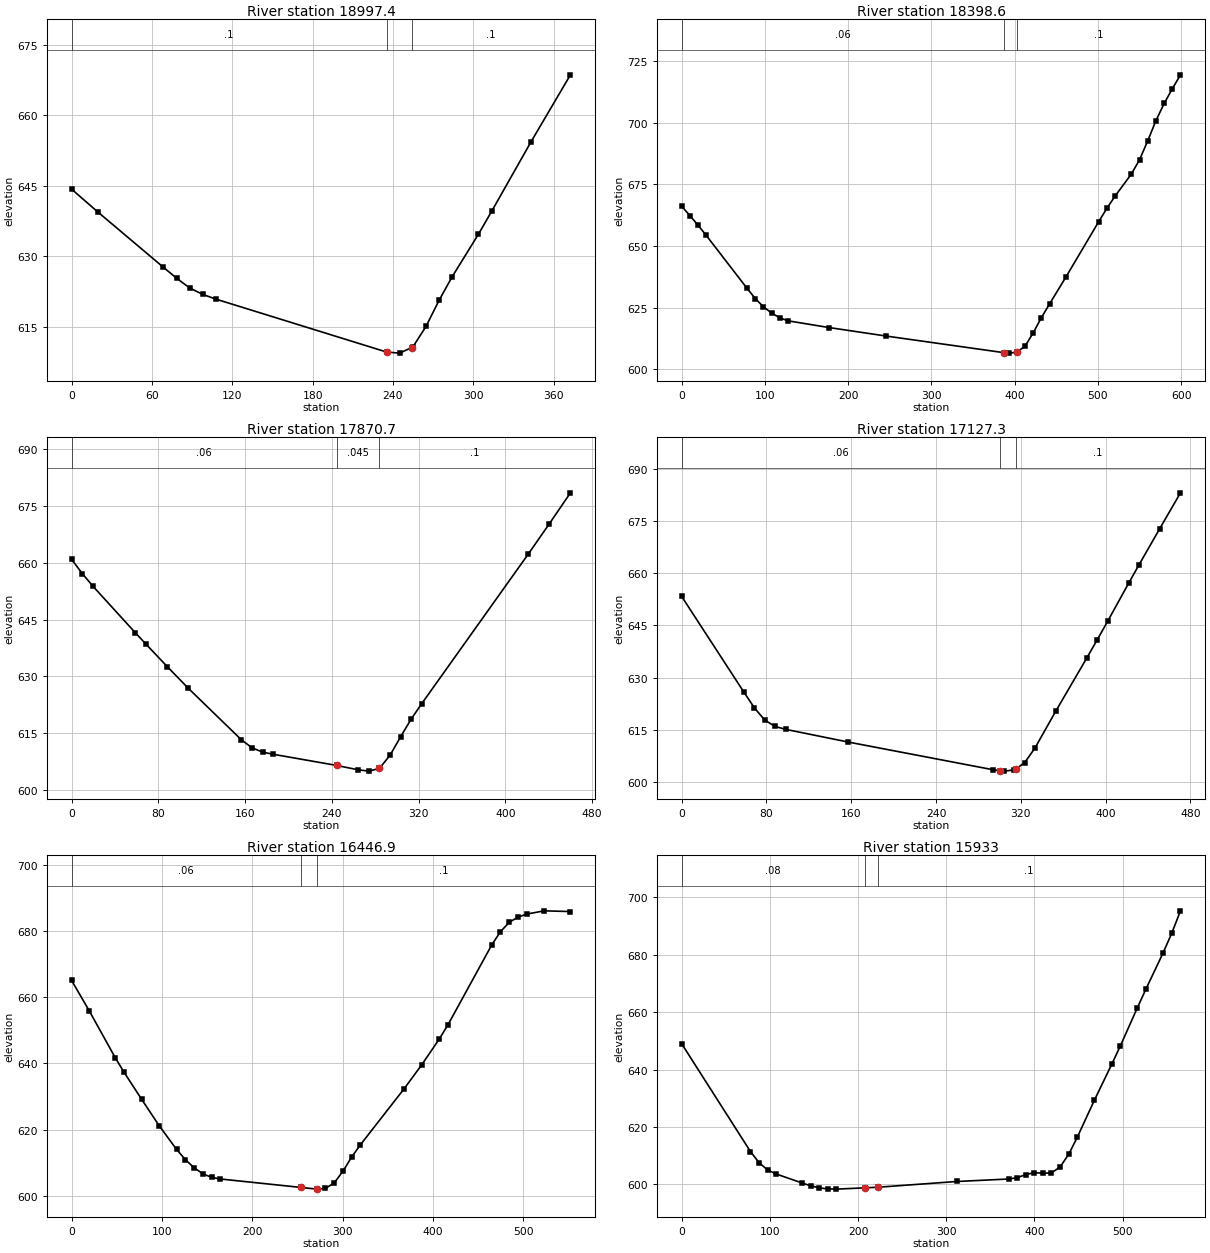
Type RM Length L Ch R = 1 ,18997.4 ,580.4,598.8,617.3
XS GIS Cut Line= 2
     1629172.621       557281.07     1629408.732      556992.875
#Sta/Elev= 18
       0  644.24    19.6  639.38    68.6  627.61    78.4   625.3    88.2  623.21
      98  621.84   107.8  620.84   235.3  609.58   245.1  609.35     254  610.54
   254.9  610.66   264.7  615.02   274.5  620.59   284.3  625.62   303.9  634.66
   313.7   639.5   343.2  654.33   372.6  668.57
#Mann= 3 , 0 , 0
       0      .1       0   235.3    .045       0     254      .1       0
Bank Sta=235.3,254
XS Rating Curve= 0 ,0
Exp/Cntr=0.3,0.1

Type RM Length L Ch R = 1 ,18398.6 ,545.6,527.9,510.1
XS GIS Cut Line= 2
     1629321.927       557531.07     1629919.149      557482.459
#Sta/Elev= 30
       0  666.09     9.8  662.34    19.6  658.43    29.5  654.29    78.6  632.82
    88.4  628.71    98.2  625.38     108  622.86   117.9   620.9   127.7  619.69
   176.8  616.97   245.6  613.52   387.7  606.76   392.9   606.6   402.7  606.96
   412.6  609.47   422.4  614.88   432.2  621.02     442  626.57   461.7  637.48
     501  659.87   510.8  665.24   520.6  670.19   540.3  679.17   550.1  684.97
   559.9  692.62   569.7  700.73   579.6  707.72   589.4  713.67   599.2  719.32
#Mann= 3 , 0 , 0
       0     .06       0   387.7    .045       0   402.7      .1       0
Bank Sta=387.7,402.7
XS Rating Curve= 0 ,0
Exp/Cntr=0.3,0.1

Type RM Length L Ch R = 1 ,17870.7 ,757.5,743.4,728.6
XS GIS Cut Line= 2
     1629728.177      558152.597     1630033.732      557808.847
#Sta/Elev= 22
       0   660.9     9.8  657.17    19.6  653.83    58.7  641.54    68.5  638.53
    88.1   632.6   107.6  626.85   156.6  613.23   166.4  611.12   176.1  609.99
   185.9  609.42   244.6  606.46   264.2  605.32     274  604.97   283.8  605.69
   293.6  609.16   303.4  614.07   313.1  618.73   322.9  622.83   420.8  662.21
   440.4  670.28   459.9  678.48
#Mann= 3 , 0 , 0
       0     .06       0   244.6    .045       0   283.8      .1       0
Bank Sta=244.6,283.8
XS Rating Curve= 0 ,0
Exp/Cntr=0.3,0.1

Type RM Length L Ch R = 1 ,17127.3 ,694.3,680.4,666.2
XS GIS Cut Line= 2
     1630544.149      558524.125     1630585.816      558055.375
#Sta/Elev= 22
       0   653.3    58.8  625.76    68.6  621.28    78.4  617.77    88.2  615.93
      98  615.11   156.9  611.47   294.1  603.48     300  603.25   303.9   603.1
   313.7  603.44     315  603.71   323.5  605.49   333.3  609.73     353  620.36
   382.4  635.71   392.2  640.92     402  646.22   421.6  657.04   431.4  662.34
     451  672.76   470.6  683.07
#Mann= 3 , 0 , 0
       0     .06       0     300    .045       0     315      .1       0
Bank Sta=300,315
XS Rating Curve= 0 ,0
Exp/Cntr=0.3,0.1

Type RM Length L Ch R = 1 ,16446.9 ,502.9,513.9,523.7
XS GIS Cut Line= 2
     1631367.066       558374.82     1631086.528      557899.401
#Sta/Elev= 30
       0  665.03    19.4  655.92    48.4  641.66    58.1  637.29    77.5  629.15
    96.8  621.23   116.2  614.01   125.9  610.95   135.6  608.48   145.3  606.66
     155  605.59   164.6   605.1   253.6  602.56   271.2  602.04   280.8  602.25
   290.5  603.88   300.2  607.42   309.9  611.72   319.6  615.43     368  632.35
   387.4  639.55   406.8  647.33   416.4   651.6   464.9  675.74   474.5  679.72
   484.2  682.56   493.9  684.14   503.6  685.06     523  686.05     552  685.83
#Mann= 3 , 0 , 0
       0     .06       0   253.6    .045       0   271.2      .1       0
Bank Sta=253.6,271.2
XS Rating Curve= 0 ,0
Exp/Cntr=0.3,0.1

Type RM Length L Ch R = 1 ,15933   ,529.1,525.4,518.3
XS GIS Cut Line= 2
     1631676.094      558201.209     1631617.066      557638.709
#Sta/Elev= 30
       0  648.98      78  611.46    87.8  607.56    97.5  605.03   107.3  603.63
   136.5  600.51   146.3  599.52     156   598.8   165.8  598.44   175.5  598.37
   207.5  598.82   222.5  599.03     312  601.03   370.6  601.89   380.3  602.33
   390.1  603.42   399.8  604.11   409.6  603.91   419.3  604.01   429.1  606.08
   438.8  610.46   448.6  616.44   468.1   629.4   487.6  641.79   497.3  648.14
   516.8  661.56   526.6  668.11   546.1  680.73   555.8  687.52   565.6  695.24
#Mann= 3 , 0 , 0
       0     .08       0   207.5    .045       0   222.5      .1       0
Bank Sta=207.5,222.5
XS Rating Curve= 0 ,0
Exp/Cntr=0.3,0.1

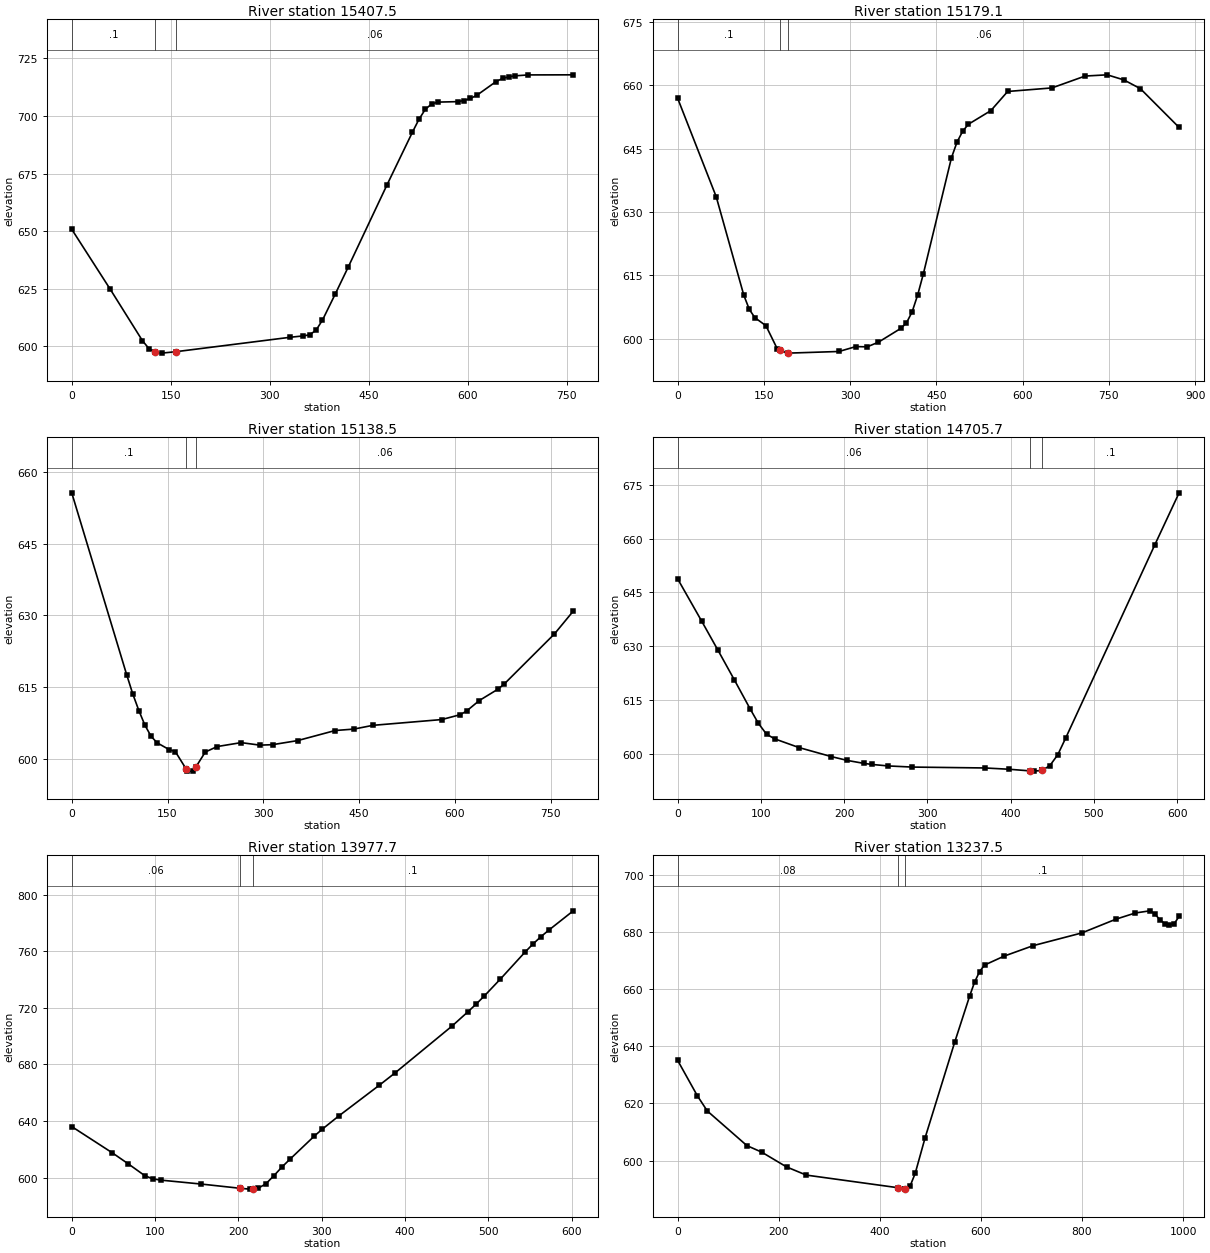
Type RM Length L Ch R = 1 ,15407.5 ,233.4,228.4,227.7
XS GIS Cut Line= 2
     1632058.038      558159.542     1631957.344       557406.07
#Sta/Elev= 30
       0  650.77    58.5  624.65   107.2  602.35     117  598.94   126.7   597.3
   136.4  596.96   157.3  597.56   331.4  603.86   350.8  604.44   360.6  604.92
   370.3  606.91   380.1  611.33   399.6  622.74   419.1  634.36   477.5  669.84
   516.5  693.02   526.3  698.56     536  702.92   545.8   705.3   555.5  706.04
   584.8  706.24   594.5   706.7   604.2  707.61     614  708.99   643.2  714.96
     653  716.31   662.7  717.06   672.5  717.46     692  717.85   760.2  717.89
#Mann= 3 , 0 , 0
       0      .1       0   126.7    .045       0   157.3     .06       0
Bank Sta=126.7,157.3
XS Rating Curve= 0 ,0
Exp/Cntr=0.3,0.1

Type RM Length L Ch R = 1 ,15179.1 ,41.4,40.6,39.5
XS GIS Cut Line= 4
     1632211.528      558128.567     1632270.121       557986.64
     1632085.041      557609.077      1632085.69      557310.998
#Sta/Elev= 30
       0  656.99    67.2  633.63   115.2   610.3   124.8  606.95   134.4     605
   153.6  603.11   173.1  597.69   177.3  597.24   192.3  596.61   280.7     597
     310  598.16   329.6   598.1   349.1  599.19   388.2  602.47     398  603.77
   407.8  606.37   417.6  610.43   427.4   615.4   476.2  642.86     486  646.61
   495.8  649.16   505.6   650.8   544.7  654.03     574  658.57     651  659.41
   708.6  662.22   747.1  662.51     776  661.31   804.8  659.23   872.1  650.05
#Mann= 3 , 0 , 0
       0      .1       0   177.3    .045       0   192.3     .06       0
Bank Sta=177.3,192.3
XS Rating Curve= 0 ,0
Exp/Cntr=0.3,0.1

Type RM Length L Ch R = 1 ,15138.5 ,398.3,432.8,467
XS GIS Cut Line= 4
     1632251.892      558119.453     1632311.788      557978.828
     1632258.403      557879.869     1632316.593      557363.082
#Sta/Elev= 30
       0  655.62      86   617.6    95.5   613.6   105.1   610.1   114.6  607.04
   124.2  604.73   133.7  603.36   152.8  601.92   162.2  601.52   178.9  597.94
     181  597.44   190.3  597.46   193.9   598.2   209.1  601.43   227.8  602.58
   265.3   603.4   294.7  602.87   314.4  602.97   353.6  603.82   412.5  605.93
   441.9  606.23   471.4  607.01   579.3  608.22   608.7  609.25   618.5  610.03
   638.2   612.2   667.6  614.59   677.4  615.68   755.9  626.13   785.3  630.89
#Mann= 3 , 0 , 0
       0      .1       0   178.9    .045       0   193.9     .06       0
Bank Sta=178.9,193.9
XS Rating Curve= 0 ,0
Exp/Cntr=0.3,0.1

Type RM Length L Ch R = 1 ,14705.7 ,724.2,728.1,731.9
XS GIS Cut Line= 2
     1632325.399      558176.903     1632814.982      557826.209
#Sta/Elev= 26
       0  648.79    29.1  636.91    48.6  628.83      68  620.69    87.4  612.42
    97.1  608.48   106.8  605.49   116.6  604.19   145.7  601.77   184.6  599.25
     204  598.17   223.4  597.37   233.1  597.07   252.6  596.65   281.7  596.33
   369.1  596.08   398.2  595.72     423  595.27   427.4   595.2   437.1  595.38
     438   595.5   446.8  596.67   456.5  599.76   466.2  604.51   573.1  658.28
   602.2  672.73
#Mann= 3 , 0 , 0
       0     .06       0     423    .045       0     438      .1       0
Bank Sta=423,438
XS Rating Curve= 0 ,0
Exp/Cntr=0.3,0.1

Type RM Length L Ch R = 1 ,13977.7 ,735.9,740.2,757.7
XS GIS Cut Line= 2
     1632666.545      558689.924     1633205.451      558421.536
#Sta/Elev= 30
       0  636.02    48.6  617.49      68   609.6    87.4  601.41    97.1  599.06
   106.8  598.16   155.4  595.37   202.2  592.37   213.6  591.78   217.2  591.97
   223.3  592.28     233  595.51   242.8  601.37   252.5  607.53   262.2  613.08
   291.3  629.38     301  634.31   320.4  643.46     369  665.18   388.4  674.12
   456.4  707.07   475.8  717.33   485.5   722.7   495.2  728.37   514.6  740.41
   543.8  759.23   553.5  765.08   563.2  770.34   572.9  775.08     602  788.62
#Mann= 3 , 0 , 0
       0     .06       0   202.2    .045       0   217.2      .1       0
Bank Sta=202.2,217.2
XS Rating Curve= 0 ,0
Exp/Cntr=0.3,0.1

Type RM Length L Ch R = 1 ,13237.5 ,717.8,701.8,671.2
XS GIS Cut Line= 3
     1632836.684      559269.785     1633426.962      559127.424
     1633728.455      558888.116
#Sta/Elev= 30
       0  635.05    39.2  622.61    58.8  617.32   137.1  605.21   166.5  602.92
   215.5  597.76   254.6   594.9   435.7  590.49   450.5  589.99   450.7  590.01
   460.3  591.21   470.1  595.54   489.7     608   548.4  641.51   577.8  657.55
   587.6  662.44   597.4  666.08   607.2  668.36   645.7  671.47   703.4  675.15
   799.7   679.6     867   684.4   905.5  686.58   934.4  687.33     944   686.3
   953.6  684.27   963.3  682.89   972.9   682.5   982.5  682.85   992.1  685.39
#Mann= 3 , 0 , 0
       0     .08       0   435.7    .045       0   450.7      .1       0
Bank Sta=435.7,450.7
XS Rating Curve= 0 ,0
Exp/Cntr=0.3,0.1

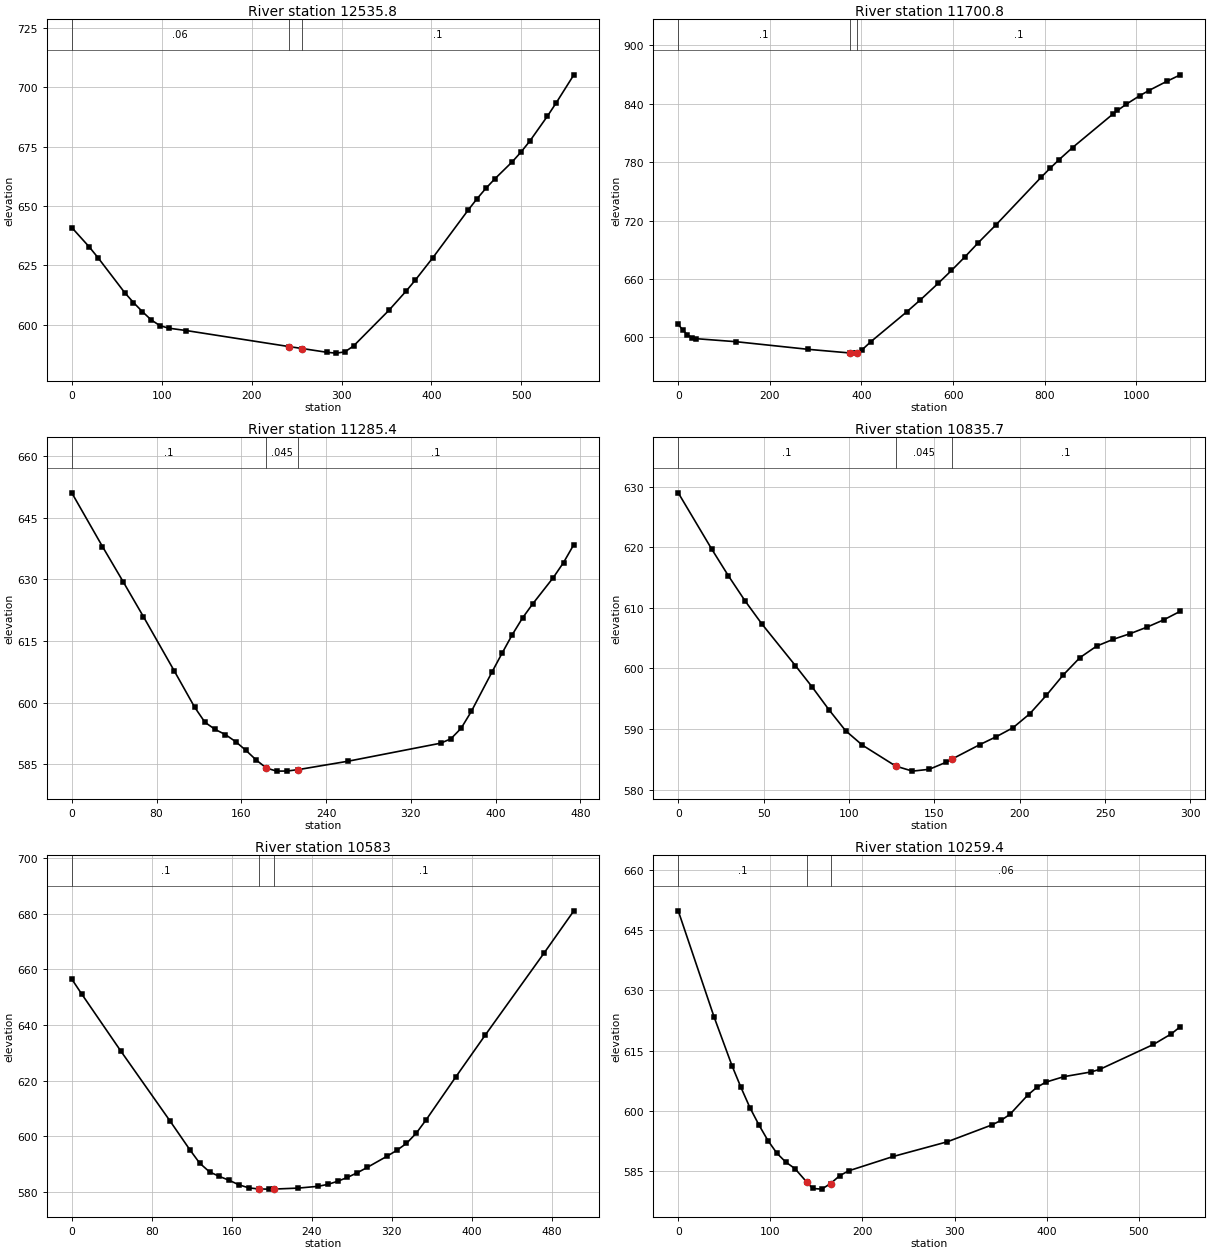
Type RM Length L Ch R = 1 ,12535.8 ,801.1,834.9,867.1
XS GIS Cut Line= 2
     1633357.517      559953.813     1633682.882      559500.095
#Sta/Elev= 30
       0  640.98    19.6  632.74    29.4  628.17    58.8  613.61    68.6  609.42
    78.4  605.63    88.2  602.15      98  599.69   107.8  598.63   127.3  597.63
   241.3   590.9   256.3  590.06   284.1  588.46   293.8  588.13   303.6  588.63
   313.4  591.17   352.6  606.12   372.2  614.41     382  618.85   401.6  628.32
   440.8  648.33   450.6  653.07   460.4  657.43   470.2  661.36   489.8  668.62
   499.6  672.75   509.4  677.37   528.9  687.82   538.7  693.44   558.3  705.22
#Mann= 3 , 0 , 0
       0     .06       0   241.3    .045       0   256.3      .1       0
Bank Sta=241.3,256.3
XS Rating Curve= 0 ,0
Exp/Cntr=0.3,0.1

Type RM Length L Ch R = 1 ,11700.8 ,411.1,415.5,417.9
XS GIS Cut Line= 3
     1633524.926      560085.304     1634142.629      560303.317
      1634577.01      560227.665
#Sta/Elev= 30
       0  613.36     9.8   607.6    19.6  602.76    29.3  599.82    39.1  598.64
   127.1  595.49   283.5   587.7   375.4  583.92   381.3  583.79   390.4  584.38
   400.8  586.97   420.4  595.52   498.6  626.12     528  638.25   567.1  655.34
   596.4   668.7   625.7  682.61     655  697.25   694.2  715.86   792.2  764.49
   811.8  773.73   831.4  782.57   860.8  795.01     949  829.47   958.8  833.07
   978.4  839.64  1007.8  848.38  1027.4   853.6  1066.6  863.06    1096  869.72
#Mann= 3 , 0 , 0
       0      .1       0   375.4    .045       0   390.4      .1       0
Bank Sta=375.4,390.4
XS Rating Curve= 0 ,0
Exp/Cntr=0.3,0.1

Type RM Length L Ch R = 1 ,11285.4 ,452.7,449.7,447.6
XS GIS Cut Line= 2
     1633423.489      560304.507     1633840.156      560530.202
#Sta/Elev= 29
       0   651.1      29     638    48.4  629.48    67.7   620.9    96.7  607.72
     116  598.85   125.7  595.18   135.4  593.43   145.1  592.17   154.7  590.46
   164.4  588.34   174.1  585.99   183.7  584.03   193.4  583.28   203.1   583.3
   213.6  583.64   261.1  585.71   348.2  590.09   357.8  591.15   367.5  593.72
   377.2  597.86   396.5  607.36   406.2  612.04   415.8  616.54   425.5  620.62
   435.2  624.08   454.5  630.44   464.2  634.12   473.9   638.5
#Mann= 3 , 0 , 0
       0      .1       0   183.7    .045       0   213.6      .1       0
Bank Sta=183.7,213.6
XS Rating Curve= 0 ,0
Exp/Cntr=0.3,0.1

Type RM Length L Ch R = 1 ,10835.7 ,252.4,252.7,253
XS GIS Cut Line= 2
     1633268.385      560711.033     1633533.142      560839.071
#Sta/Elev= 28
       0  628.96    19.6  619.68    29.4  615.26    39.2  611.11      49  607.32
    68.6  600.46    78.4  596.94    88.2   593.2      98  589.72   107.8  587.34
   127.4  583.87   137.2  583.04     147  583.34   156.8  584.49   160.1  584.99
   176.5  587.39   186.3  588.72   196.1   590.2   205.9   592.5   215.7  595.57
   225.5   598.9   235.3  601.77   245.1  603.67   254.9   604.8   264.7  605.72
   274.5  606.79   284.3  607.99   294.1  609.42
#Mann= 3 , 0 , 0
       0      .1       0   127.4    .045       0   160.1      .1       0
Bank Sta=127.4,160.1
XS Rating Curve= 0 ,0
Exp/Cntr=0.3,0.1

Type RM Length L Ch R = 1 ,10583   ,320.8,323.6,326.1
XS GIS Cut Line= 2
     1633120.413      560916.901     1633569.323      561141.313
#Sta/Elev= 30
       0  656.53     9.8  651.23    49.2  630.56    98.4  605.41   118.1  595.12
   127.9  590.32   137.8  587.17   147.6  585.56   157.4  584.16   167.3  582.51
   177.1  581.44   187.3  581.04   196.8  580.99   202.3  581.01   226.3  581.36
     246  581.99   255.9  582.69   265.7   583.8   275.5   585.2   285.4  586.87
   295.2  588.77   314.9  592.77   324.7  594.89   334.6  597.44   344.4  601.13
   354.3  605.95   383.8   621.3   413.3  636.38   472.4  666.03   501.9  681.08
#Mann= 3 , 0 , 0
       0      .1       0   187.3    .045       0   202.3      .1       0
Bank Sta=187.3,202.3
XS Rating Curve= 0 ,0
Exp/Cntr=0.3,0.1

Type RM Length L Ch R = 1 ,10259.4 ,874.7,880.1,879.2
XS GIS Cut Line= 2
     1632986.857      561148.257     1633445.191      561443.396
#Sta/Elev= 30
       0  649.79    38.9  623.39    58.4  611.24    68.1  605.85    77.9  600.78
    87.6  596.52    97.4  592.62   107.1  589.48   116.8  587.26   126.6  585.67
   139.8  582.22     146   580.7   155.8  580.54   165.5  581.94   175.2  583.87
     185  585.09   233.6  588.68     292  592.31   340.7  596.53   350.4  597.64
   360.2  599.16   379.6  603.97   389.4  605.88   399.1  607.16   418.6  608.52
   447.8  609.68   457.5  610.32   515.9  616.54   535.4  619.18   545.1  620.97
#Mann= 3 , 0 , 0
       0      .1       0   139.8    .045       0   165.5     .06       0
Bank Sta=139.8,165.5
XS Rating Curve= 0 ,0
Exp/Cntr=0.3,0.1