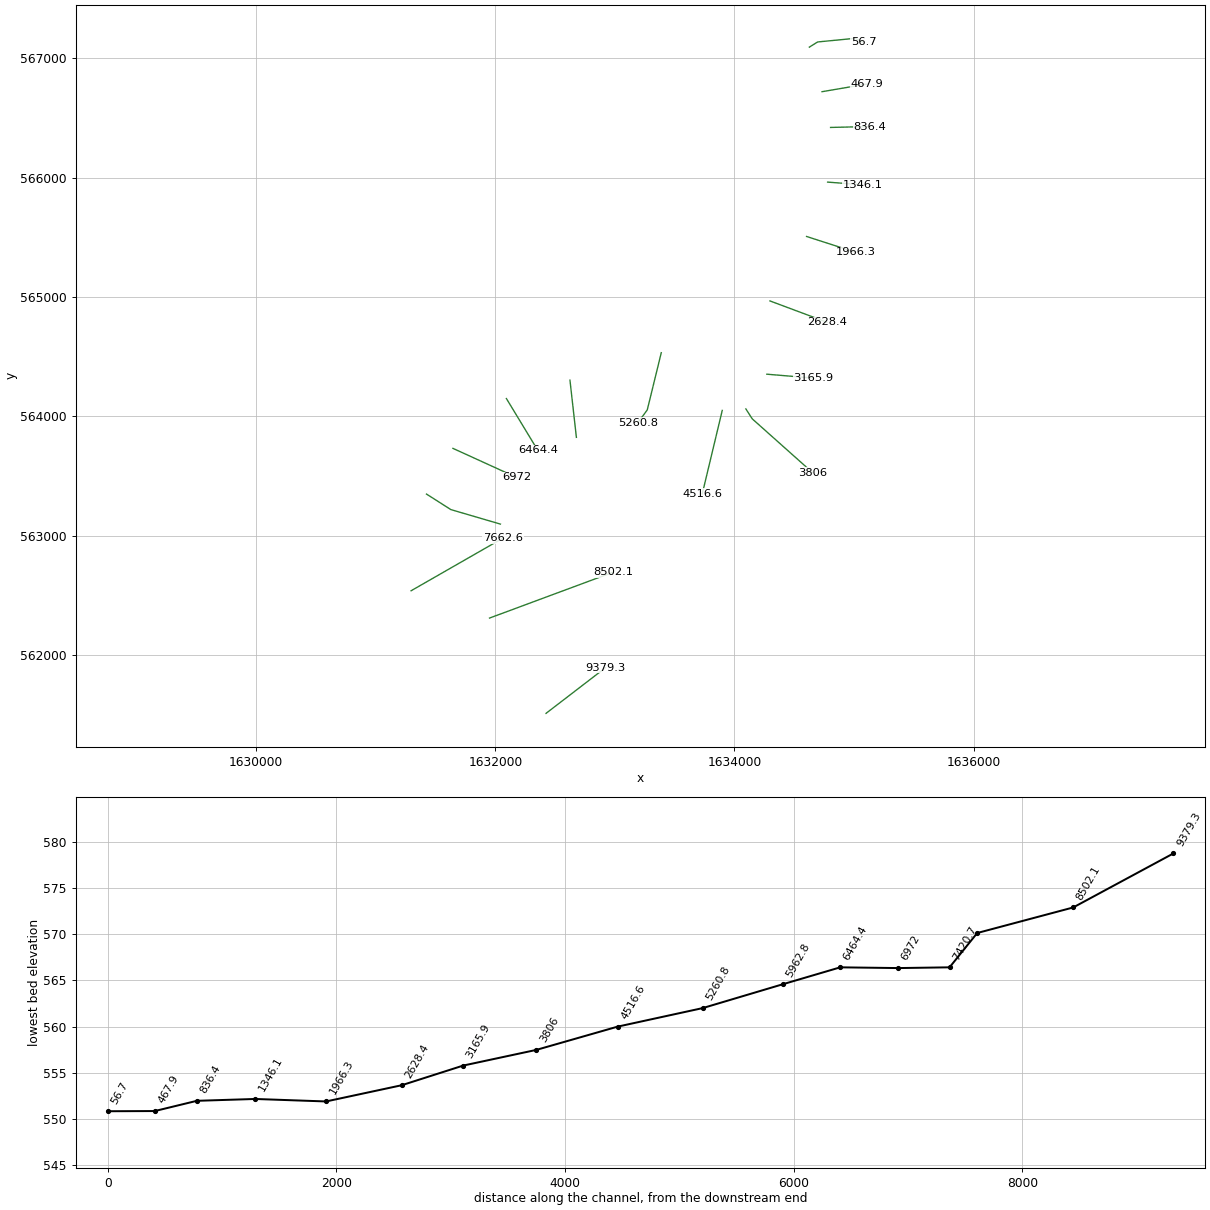
HEC-RAS study BryanCr.prj: BryanCr

--- BryanCr.g01 (geometry) --- (continued)

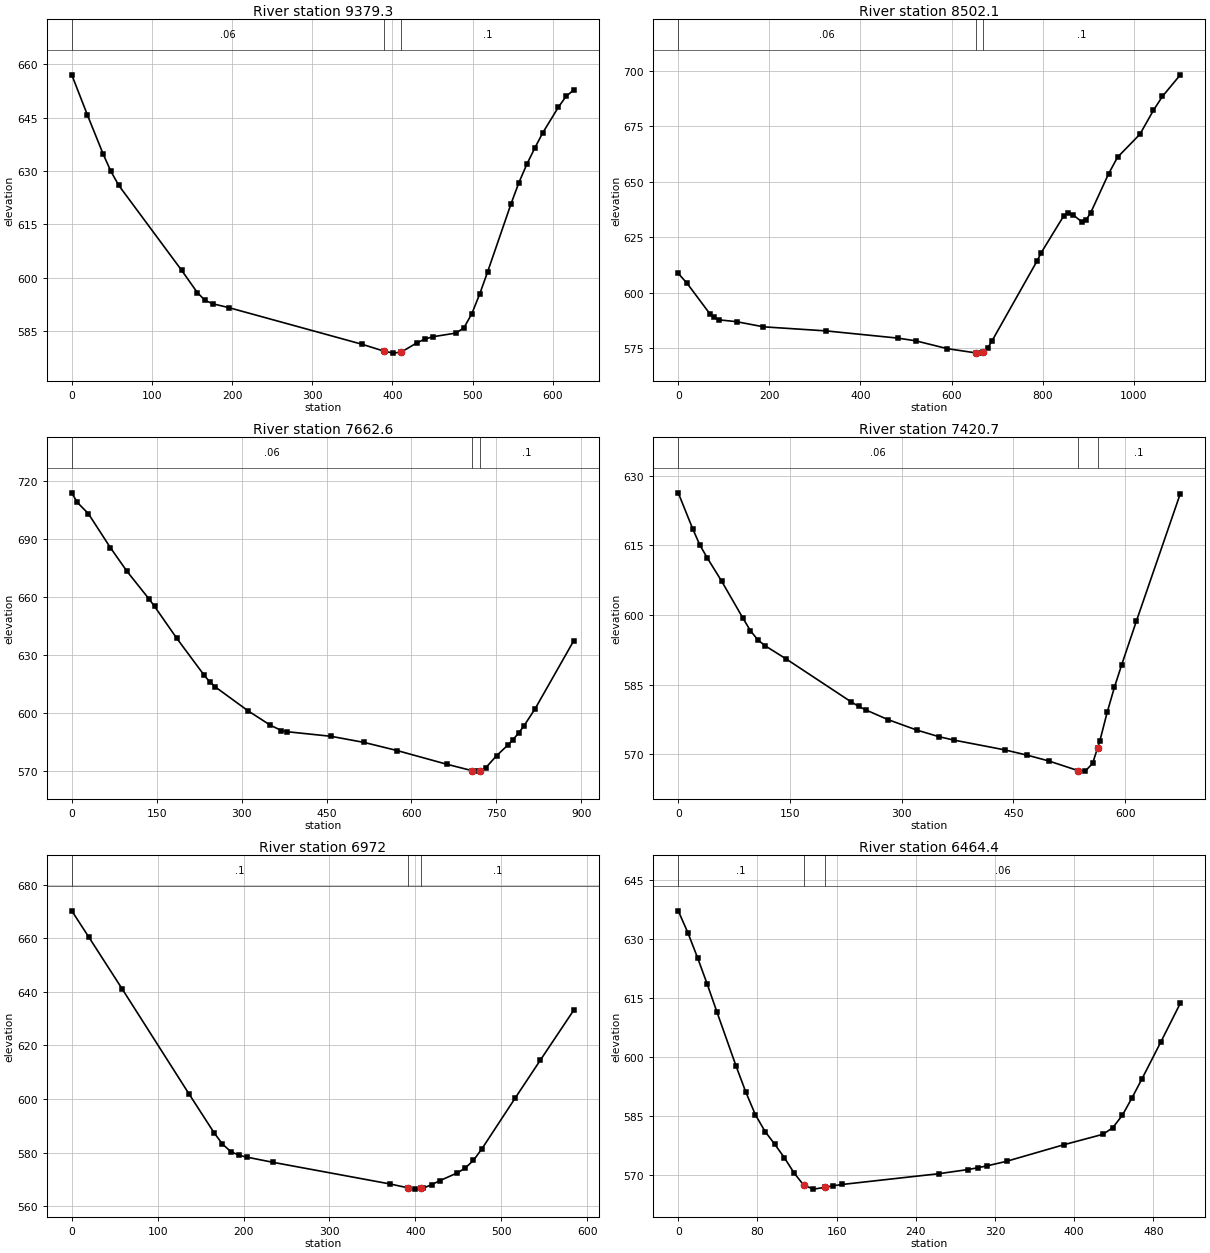
Type RM Length L Ch R = 1 ,9379.3  ,884.1,877.1,869.8
XS GIS Cut Line= 2
     1632423.489      561509.368     1632920.017      561891.313
#Sta/Elev= 30
       0  657.02    19.6  645.68    39.2  634.72    48.9  629.84    58.7  625.91
     137  602.08   156.6  595.81   166.4  593.58   176.2  592.63   195.8  591.57
   362.2  581.26   389.9   579.3   401.3  578.77   411.1  579.08   430.7  581.67
   440.5   582.7   450.2  583.37   479.6  584.42   489.4  585.93   499.2   589.9
     509  595.42   518.8  601.61   548.1   620.8   557.9  626.74   567.7  631.86
   577.5  636.35   587.3   640.6   606.9  647.85   616.6  650.94   626.4   652.8
#Mann= 3 , 0 , 0
       0     .06       0   389.9    .045       0   411.1      .1       0
Bank Sta=389.9,411.1
XS Rating Curve= 0 ,0
Exp/Cntr=0.3,0.1

Type RM Length L Ch R = 1 ,8502.1  ,835.5,839.5,842.9
XS GIS Cut Line= 2
     1631951.111      562308.255     1632984.097      562692.369
#Sta/Elev= 30
       0  608.83    19.7  604.28    68.9  590.76    78.7  588.97    88.6  587.92
   127.9  587.08     187  584.76   324.7  582.92   482.2  579.67   521.5  578.45
   590.4  574.93   653.8     573   659.3  572.91   668.8  573.28     679  575.12
   688.8  578.44   787.2  614.25     797  618.23   846.2  634.74   856.1  636.21
   865.9  635.34   885.6  632.09   895.4  632.99   905.3  636.11   944.6  653.68
   964.3  661.15  1013.5  671.52    1043  682.24  1062.7  688.51  1102.1  698.27
#Mann= 3 , 0 , 0
       0     .06       0   653.8    .045       0   668.8      .1       0
Bank Sta=653.8,668.8
XS Rating Curve= 0 ,0
Exp/Cntr=0.3,0.1

Type RM Length L Ch R = 1 ,7662.6  ,260.2,242,223.6
XS GIS Cut Line= 2
     1631295.017      562537.146     1632063.958      562978.828
#Sta/Elev= 30
       0  714.04     9.7   709.1    29.2  703.32    68.2  685.69    97.4   673.5
   136.4  659.18   146.2  655.32   185.2  638.92   233.9  619.71   243.6  616.36
   253.4  613.69   311.8  601.23   350.8  593.88   370.3  591.13     380  590.53
     458  588.14   516.5  584.97   574.9  580.76   662.6  573.68   706.3  570.44
   711.4  570.14   721.3  570.28   730.8  571.75   750.3   578.1   769.8   583.5
   779.6  586.48   789.3  589.87   799.1  593.72   818.6  602.49   886.8  637.65
#Mann= 3 , 0 , 0
       0     .06       0   706.3    .045       0   721.3      .1       0
Bank Sta=706.3,721.3
XS Rating Curve= 0 ,0
Exp/Cntr=0.3,0.1

Type RM Length L Ch R = 1 ,7420.7  ,451.6,448.6,444.9
XS GIS Cut Line= 3
     1631423.767      563347.751      1631627.76      563217.543
     1632042.257      563096.015
#Sta/Elev= 30
       0  626.29    19.4  618.55      29  615.07    38.7  612.36    58.1  607.33
    87.1  599.26    96.8  596.66   106.5  594.72   116.2  593.43   145.2  590.52
   232.3   581.3     242  580.37   251.8  579.59   281.3  577.52   320.5  575.24
     350  573.83   369.6  573.11   438.4  570.99   467.8  569.88   497.2  568.62
   536.5  566.54   546.3  566.42   556.2  568.07   562.9  571.39     566  572.93
   575.8  579.06   585.6  584.49   595.4  589.35     615  598.68     674  626.12
#Mann= 3 , 0 , 0
       0     .06       0   536.5    .045       0   562.9      .1       0
Bank Sta=536.5,562.9
XS Rating Curve= 0 ,0
Exp/Cntr=0.3,0.1

Type RM Length L Ch R = 1 ,6972    ,520.9,507.6,493.5
XS GIS Cut Line= 2
     1631645.555      563730.564     1632177.239      563487.508
#Sta/Elev= 24
       0  670.18    19.5  660.55    58.5  641.13   136.4  601.92   165.6  587.42
   175.4  583.17   185.1  580.35   194.9  578.95   204.6  578.23   233.8  576.37
   370.2  568.29     392  566.79   399.5  566.34     407   566.6   409.2  566.68
     419  568.02   428.7  569.51   448.2   572.3   457.9  574.13   467.7  577.08
   477.4  581.31   516.4  600.37   545.6  614.47   584.6  633.17
#Mann= 3 , 0 , 0
       0      .1       0     392    .045       0     407      .1       0
Bank Sta=392,407
XS Rating Curve= 0 ,0
Exp/Cntr=0.3,0.1

Type RM Length L Ch R = 1 ,6464.4  ,510.7,501.6,492.1
XS GIS Cut Line= 2
      1632092.17      564148.533     1632354.757      563714.505
#Sta/Elev= 30
       0  637.26     9.8  631.65    19.5  625.34    29.3  618.59      39  611.58
    58.5   597.7    68.3  591.11      78  585.33    87.8  581.07    97.6  577.82
   107.3  574.39   117.1  570.52   126.8  567.42   136.6  566.42   148.1  566.86
   156.1  567.26   165.8  567.61   263.4  570.35   292.7   571.4   302.4  571.85
   312.2  572.35   331.7   573.5   390.2  577.76   429.2  580.38     439  582.04
   448.8  585.24   458.5  589.66   468.3  594.36   487.8  603.97   507.3  613.73
#Mann= 3 , 0 , 0
       0      .1       0   126.8    .045       0   148.1     .06       0
Bank Sta=126.8,148.1
XS Rating Curve= 0 ,0
Exp/Cntr=0.3,0.1

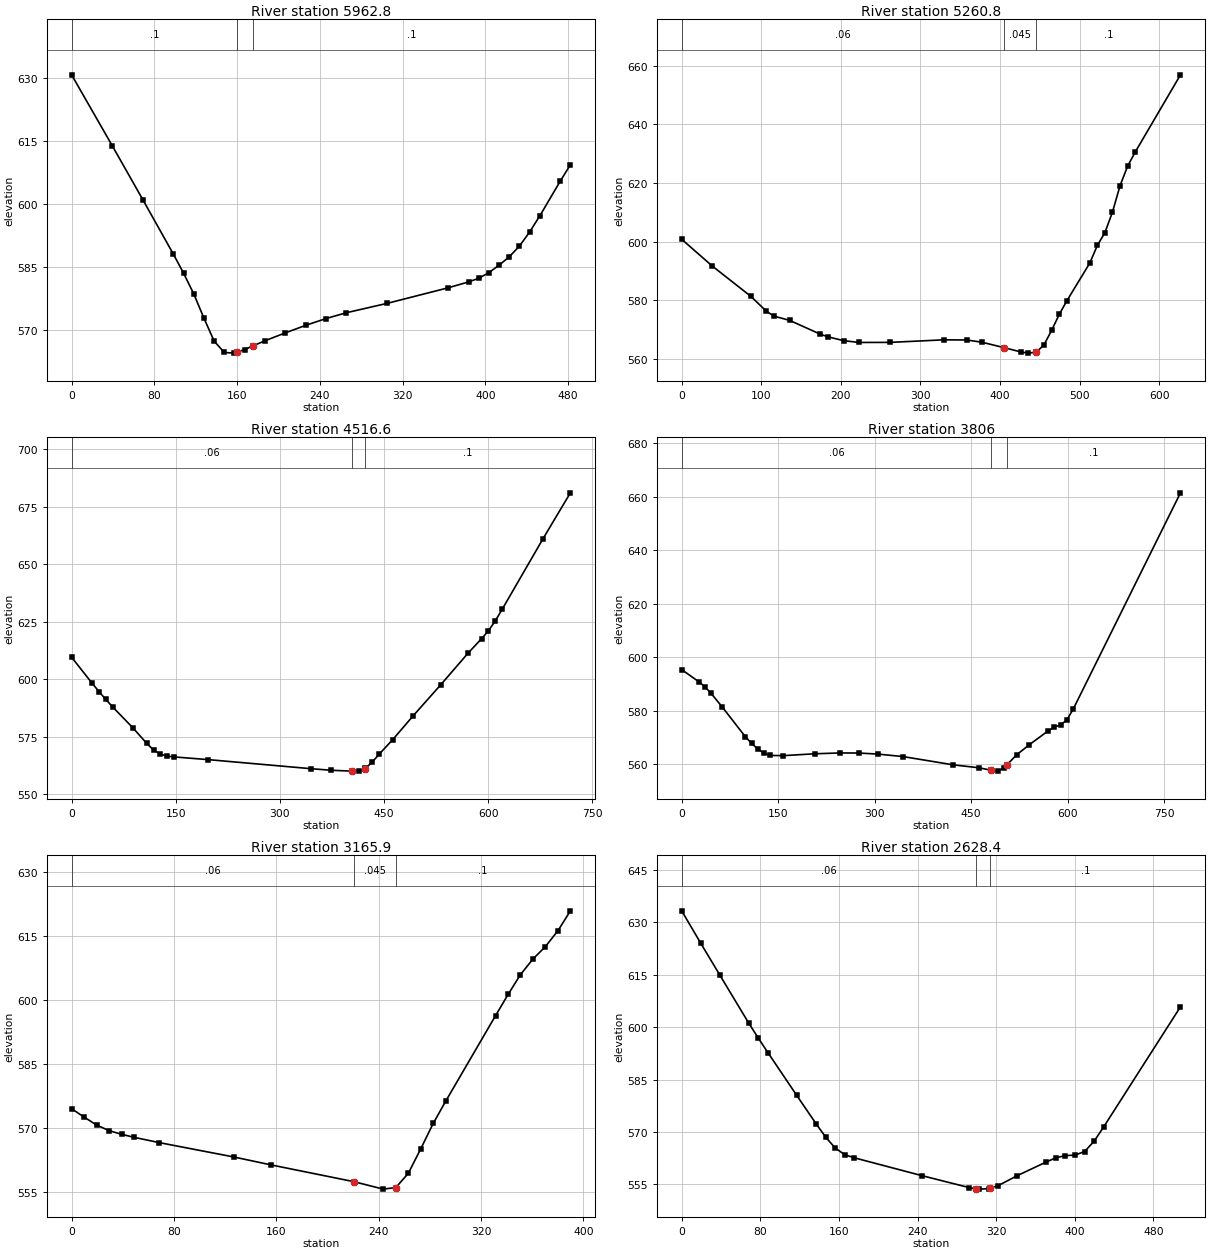
Type RM Length L Ch R = 1 ,5962.8  ,711.5,702.1,692.2
XS GIS Cut Line= 2
     1632623.885      564302.318     1632677.704      563823.151
#Sta/Elev= 30
       0  630.82    39.4   613.9    68.9  601.09    98.4  588.14   108.2  583.64
   118.1  578.69   127.9  572.93   137.8  567.45   147.6  564.74   157.4  564.59
   160.2  564.83   167.3  565.44   175.2  566.31     187  567.54   206.6  569.41
   226.3   571.2     246  572.82   265.7  574.21     305  576.43   364.1  580.14
   383.8  581.54   393.6   582.4   403.5  583.76   413.3  585.52   423.1  587.52
     433  590.08   442.8  593.42   452.7  597.28   472.3  605.48   482.2  609.42
#Mann= 3 , 0 , 0
       0      .1       0   160.2    .045       0   175.2      .1       0
Bank Sta=160.2,175.2
XS Rating Curve= 0 ,0
Exp/Cntr=0.3,0.1

Type RM Length L Ch R = 1 ,5260.8  ,744.6,744.2,743.5
XS GIS Cut Line= 3
     1633387.743      564532.647     1633270.555      564053.047
     1633191.719         563946.
#Sta/Elev= 30
       0  600.81    38.7  591.63    87.1  581.31   106.5  576.25   116.2  574.59
   135.5  573.18   174.2  568.45   183.9  567.55   203.3  566.26   222.6  565.64
   261.4  565.66   329.1  566.53   358.2  566.48   377.5   565.7   405.4  563.84
     426  562.41   435.6     562   445.3  562.32     455  564.75   464.7  569.74
   474.4  575.26     484   579.9   512.7  592.72   522.2  598.75   531.7   603.1
   541.2  610.13   550.7   619.1   560.2  625.76   569.7  630.54   626.6  656.89
#Mann= 3 , 0 , 0
       0     .06       0   405.4    .045       0   445.3      .1       0
Bank Sta=405.4,445.3
XS Rating Curve= 0 ,0
Exp/Cntr=0.3,0.1

Type RM Length L Ch R = 1 ,4516.6  ,685.1,710.6,733.7
XS GIS Cut Line= 2
     1633897.725      564048.706     1633730.625      563349.922
#Sta/Elev= 30
       0  609.52    29.5  598.24    39.4   594.6    49.2  591.18      59  587.95
    88.6  578.72   108.3  572.03   118.1  569.18     128  567.32   137.8  566.51
   147.6  566.17   196.8  564.99   344.5  561.06     374  560.36   403.5  559.99
   413.4     560   422.1  561.04   423.2  561.17   433.1  563.95   442.9  567.32
   462.6   573.7   492.1  584.08   531.5  597.46   570.8   611.2   590.5  617.58
   600.4     621   610.2  625.29   620.1   630.3   679.1  661.09   718.5  681.03
#Mann= 3 , 0 , 0
       0     .06       0   403.5    .045       0   422.1      .1       0
Bank Sta=403.5,422.1
XS Rating Curve= 0 ,0
Exp/Cntr=0.3,0.1

Type RM Length L Ch R = 1 ,3806    ,624.5,640.1,654.3
XS GIS Cut Line= 3
     1634095.208      564061.727      1634148.51       563978.49
     1634652.934      563527.873
#Sta/Elev= 30
       0  595.41      27   590.8    35.9  589.01    44.9  586.74    62.9  581.48
    98.8  570.36   108.6  567.86   118.4  565.72   128.2  564.12     138  563.33
   157.7  563.25   206.7  563.95   245.9  564.26   275.3  564.23   304.7  563.84
   343.9  562.91   422.3  559.81   461.5  558.74   481.2  557.79     491  557.47
   500.8  558.66   505.7  559.88   520.4  563.53     540  567.28   569.4  572.48
   579.2  573.97     589  574.71   598.8  576.67   608.6   580.7   775.2  661.45
#Mann= 3 , 0 , 0
       0     .06       0   481.2    .045       0   505.7      .1       0
Bank Sta=481.2,505.7
XS Rating Curve= 0 ,0
Exp/Cntr=0.3,0.1

Type RM Length L Ch R = 1 ,3165.9  ,543.7,537.5,531.3
XS GIS Cut Line= 2
     1634270.989      564352.526     1634659.444      564319.974
#Sta/Elev= 23
       0  574.57     9.8   572.6    19.5  570.76    29.2  569.45      39  568.59
    48.7  567.89    68.2  566.66   126.7  563.29   155.9  561.43   220.8   557.5
   243.6  555.77   253.4  556.15   263.1  559.45   272.9  565.22   282.6  571.13
   292.4  576.35   331.3  596.32   341.1  601.27   350.8  605.93   360.6  609.58
   370.3  612.48   380.1  616.19   389.8  620.83
#Mann= 3 , 0 , 0
       0     .06       0   220.8    .045       0   253.4      .1       0
Bank Sta=220.8,253.4
XS Rating Curve= 0 ,0
Exp/Cntr=0.3,0.1

Type RM Length L Ch R = 1 ,2628.4  ,660.4,662.1,663
XS GIS Cut Line= 2
     1634297.031      564966.675     1634772.291      564788.724
#Sta/Elev= 28
       0   633.3    19.5  623.97      39  614.81    68.3  601.12    78.1   596.8
    87.8  592.68   117.1  580.45   136.6   572.4   146.4  568.56   156.2   565.4
   165.9  563.49   175.7   562.6     244  557.53   292.8  554.06   299.2  553.78
   302.5  553.64   312.3  553.78   314.2  553.95   322.1  554.66   341.6  557.52
   370.8  561.39   380.6   562.6   390.4  563.24   400.1  563.37   409.9  564.39
   419.6  567.34   429.4  571.47   507.5  605.83
#Mann= 3 , 0 , 0
       0     .06       0   299.2    .045       0   314.2      .1       0
Bank Sta=299.2,314.2
XS Rating Curve= 0 ,0
Exp/Cntr=0.3,0.1

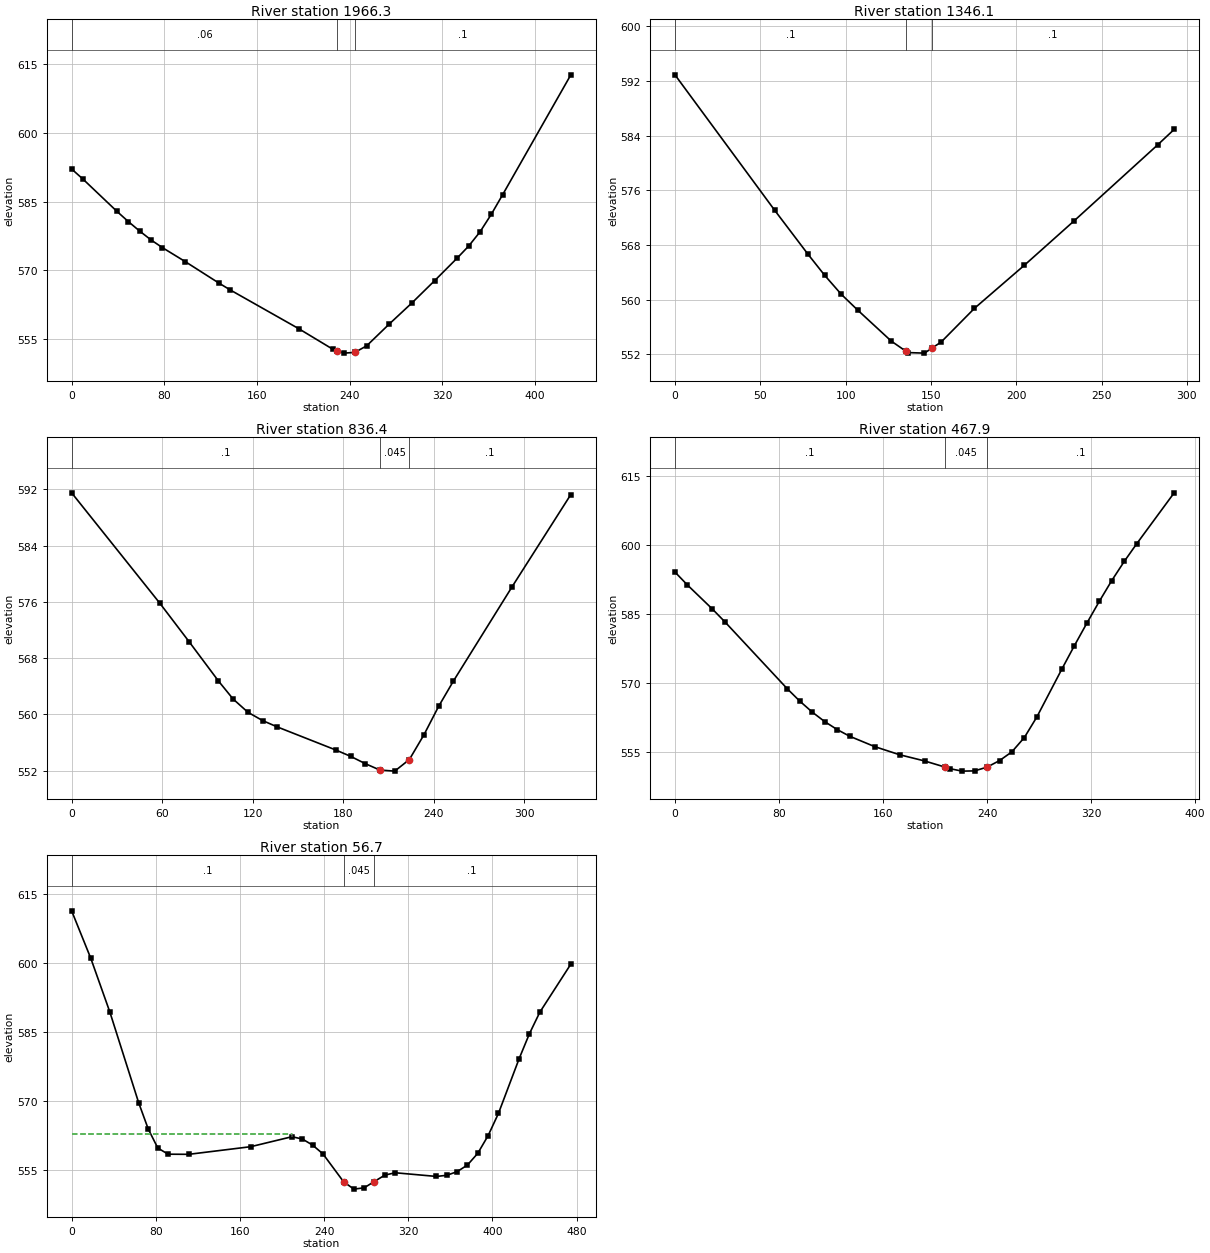
Type RM Length L Ch R = 1 ,1966.3  ,614.1,620.2,621.1
XS GIS Cut Line= 2
     1634603.021       565507.04     1635013.177      565374.661
#Sta/Elev= 25
       0  592.13     9.8  589.92    39.2  582.85      49  580.63    58.8  578.55
    68.6  576.62    78.4  574.94      98   571.9   127.3  567.17   137.1  565.67
   195.9  557.25   225.3  552.76   229.5  552.38   235.1  551.88   244.5  552.04
   254.7  553.47   274.3  558.26   293.9  562.88   313.4  567.72     333  572.69
   342.8  575.29   352.6  578.39   362.4  582.26   372.2  586.55     431  612.72
#Mann= 3 , 0 , 0
       0     .06       0   229.5    .045       0   244.5      .1       0
Bank Sta=229.5,244.5
XS Rating Curve= 0 ,0
Exp/Cntr=0.3,0.1

Type RM Length L Ch R = 1 ,1346.1  ,507.4,509.7,511.7
XS GIS Cut Line= 2
     1634779.127       565962.66     1635070.794      565940.525
#Sta/Elev= 17
       0  592.89    58.5  573.04      78  566.61    87.8  563.52    97.5  560.75
   107.2  558.42   126.8   553.9   135.5   552.4   136.5  552.23   146.2  552.15
   150.5  552.87     156  553.78   175.5  558.71   204.8  565.03     234  571.54
   282.8  582.63   292.5   584.9
#Mann= 3 , 0 , 0
       0      .1       0   135.5    .045       0   150.5      .1       0
Bank Sta=135.5,150.5
XS Rating Curve= 0 ,0
Exp/Cntr=0.3,0.1

Type RM Length L Ch R = 1 ,836.4   ,364.4,368.5,372.3
XS GIS Cut Line= 2
     1634803.867      566420.994     1635134.596      566428.806
#Sta/Elev= 19
       0  591.51    58.4  575.83    77.8  570.36    97.3  564.76     107   562.2
   116.8  560.32   126.5  559.14   136.2  558.24   175.1  554.95   184.9  554.05
   194.6  553.01   204.3   552.1   214.1  551.95   223.8   553.6   233.5  557.13
   243.2  561.16     253  564.76   291.9  578.17   330.8  591.27
#Mann= 3 , 0 , 0
       0      .1       0   204.3    .045       0   223.8      .1       0
Bank Sta=204.3,223.8
XS Rating Curve= 0 ,0
Exp/Cntr=0.3,0.1

Type RM Length L Ch R = 1 ,467.9   ,413.2,411.2,408.9
XS GIS Cut Line= 2
     1634732.773      566720.646     1635111.159      566785.577
#Sta/Elev= 30
       0  594.13     9.6  591.31    28.8  586.08    38.4   583.3    86.4  568.74
      96  566.06   105.6  563.67   115.2   561.6   124.8  559.87   134.4  558.42
   153.6  556.17   172.8   554.4     192  553.05   207.3  551.75   211.2  551.39
   220.8  550.84   230.4  550.89     240  551.71   249.6  553.13   259.1  555.03
   268.7  558.15   278.3  562.61   297.5  573.01   307.1  578.08   316.7  582.98
   326.3  587.74   335.9  592.27   345.5  596.43   355.1  600.28   383.9  611.35
#Mann= 3 , 0 , 0
       0      .1       0   207.3    .045       0     240      .1       0
Bank Sta=207.3,240
XS Rating Curve= 0 ,0
Exp/Cntr=0.3,0.1

Type RM Length L Ch R = 1 ,56.7    ,58.6,56.7,54.9
XS GIS Cut Line= 4
     1634626.108      567094.148     1634695.552      567137.551
     1635008.052      567167.933     1635079.667      567135.381
#Sta/Elev= 30
       0  611.36    18.2  601.04    36.4   589.3    63.7  569.63    72.8  563.91
    81.9  559.76    91.7  558.42   111.3  558.39   170.2  560.05   209.4  562.22
   219.3  561.72   229.1  560.39   238.9  558.48   258.5  552.42   268.3  550.82
   278.1  551.11     287  552.38   297.8  553.88   307.6  554.38   346.8  553.58
   356.6  553.83   366.4  554.62   376.2  556.06     386   558.6   395.9  562.47
   405.7   567.3   425.4  579.23   435.2  584.66     445   589.3   474.5  599.77
#Mann= 3 , 0 , 0
       0      .1       0   258.5    .045       0     287      .1       0
#XS Ineff= 2 , 0
          209.86  562.74
Permanent Ineff=
       F       F
Bank Sta=258.5,287
XS Rating Curve= 0 ,0
Exp/Cntr=0.3,0.1

Chan Stop Cuts=-1
Use User Specified Reach Order=0
Composite Channel Slope=5